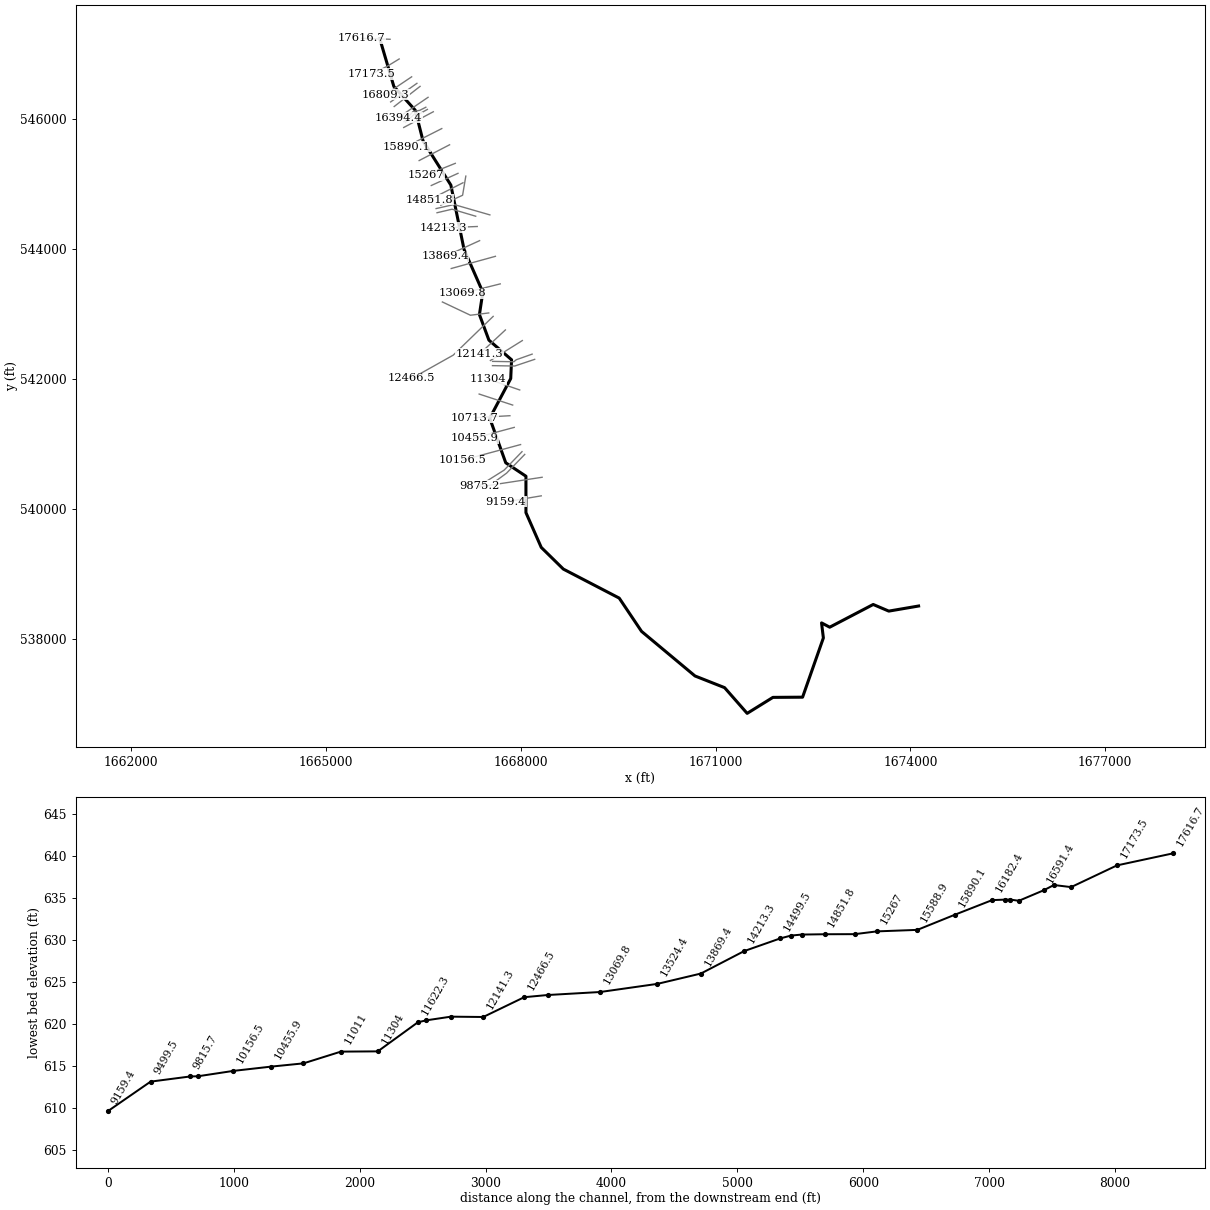
--- NP13.prj (project) ---

Proj Title=NP13
Current Plan=p01
Default Exp/Contr=0,0
English Units
Geom File=g01
Flow File=f01
Plan File=p01
BEGIN DESCRIPTION:
AMEC Environment & Infrastructure, 2013
Projection: NAD 1983 State Plane West Virginia South FIPS 4702 (US Feet)
Vertical Datum: NAVD 1988
END DESCRIPTION:
DSS Export Rating Curves= 0
DSS Export Rating Curve Sorted= 0
DSS Export Volume Flow Curves= 0
DXF OffsetX= 0
DXF OffsetY= 0
DXF ScaleX= 0
DXF ScaleY= 0

--- NP13.p01 (plan) ---

Plan Title=Floodplain
Program Version=4.00
Geom File=g01
Flow File=f01
K Sum by GR=0
Std Step Tol=0.01
Critical Tol=0.01
Num of Std Step Trials=20
Max Error Tol=0.3
Flow Tol Ratio=0.001
Split Flow NTrial=30
Split Flow Tol=0.02
Split Flow Ratio=0.02
Log Output Level=0
Friction Slope Method=1
Unsteady Friction Slope Method=2
Unsteady Bridges Friction Slope Method=1
Global Log Level=0
CheckData=False
Run HTab=0
Run UNet=0
Run PostProcess=0
UNET Theta=0
UNET Theta Warmup=0
UNET ZTol=0
UNET ZSATol=0
UNET MxIter=0
UNET MaxInSteps=0
UNET DtIC=0
UNET DtMin=0
UNET MaxCRTS=0
UNET WFStab=0
UNET SFStab=0
UNET WFX=0
UNET SFX=0
UNET DSS MLevel=0
UNET DZMax Abort=0
UNET Convert EG Bridges=0
UNET Use Existing IB Tables=0
UNET Froude Limit=0
UNET Froude Power=0
Write IC File=0
Echo Input=False
Echo Output=False
Write Detailed=0

--- NP13.f01 (steady flow) ---

Flow Title=USGS Regress. Eqn. (2010) - Western-Plateaus
Program Version=4.00
Number of Profiles=1
Profile Names=P100yr
River Rch & RM=NP13,Main      ,17616.7
    1105
River Rch & RM=NP13,Main      ,15267
    1128
River Rch & RM=NP13,Main      ,14670.2
    1133
River Rch & RM=NP13,Main      ,14213.3
    1233
River Rch & RM=NP13,Main      ,13069.8
    1270
River Rch & RM=NP13,Main      ,12652
    1271
River Rch & RM=NP13,Main      ,12466.5
    1413
River Rch & RM=NP13,Main      ,11688.3
    1419
River Rch & RM=NP13,Main      ,11011
    1446
River Rch & RM=NP13,Main      ,10156.5
    1457
River Rch & RM=NP13,Main      ,9875.2
    1599
River Rch & RM=NP13,Main      ,8091.6
    1663
River Rch & RM=NP13,Main      ,5332.1
    1703
River Rch & RM=NP13,Main      ,3904
    1774
River Rch & RM=NP13,Main      ,3679.6
    1776
River Rch & RM=NP13,Main      ,3019.1
    2477
River Rch & RM=NP13,Main      ,1236.8
    2826
Boundary for River Rch & Prof#=NP13,Main      ,1
Up Type=0
Dn Type=3
Dn Slope=0.000583

--- NP13.g01 (geometry) ---

Geom Title=USGS 3m DEM
Program Version=4.10

River Reach=NP13            ,Main
Reach XY= 30
     1665829.077      547232.728     1666046.193      546495.713
     1666375.545      546129.944     1666495.337      545658.589
     1666923.722      544978.902     1667126.847      543989.319
      1667415.91      543331.766     1667363.827      542986.714
      1667509.66      542593.485     1667858.618      542291.402
     1667845.597      542002.339     1667522.681      541392.964
     1667768.775      540706.766     1668079.972      540499.735
     1668079.972      539939.839      1668315.65      539404.683
     1668655.493       539071.35      1669516.17      538624.735
      1669859.92      538113.016     1670682.837      537426.819
     1671138.566      537247.131     1671486.222      536851.298
     1671882.951      537097.446     1672339.738      537100.442
     1672659.844      538012.141     1672631.609      538243.314
     1672757.512      538177.118     1673427.134      538526.642
     1673666.999      538424.638     1674126.133      538503.057

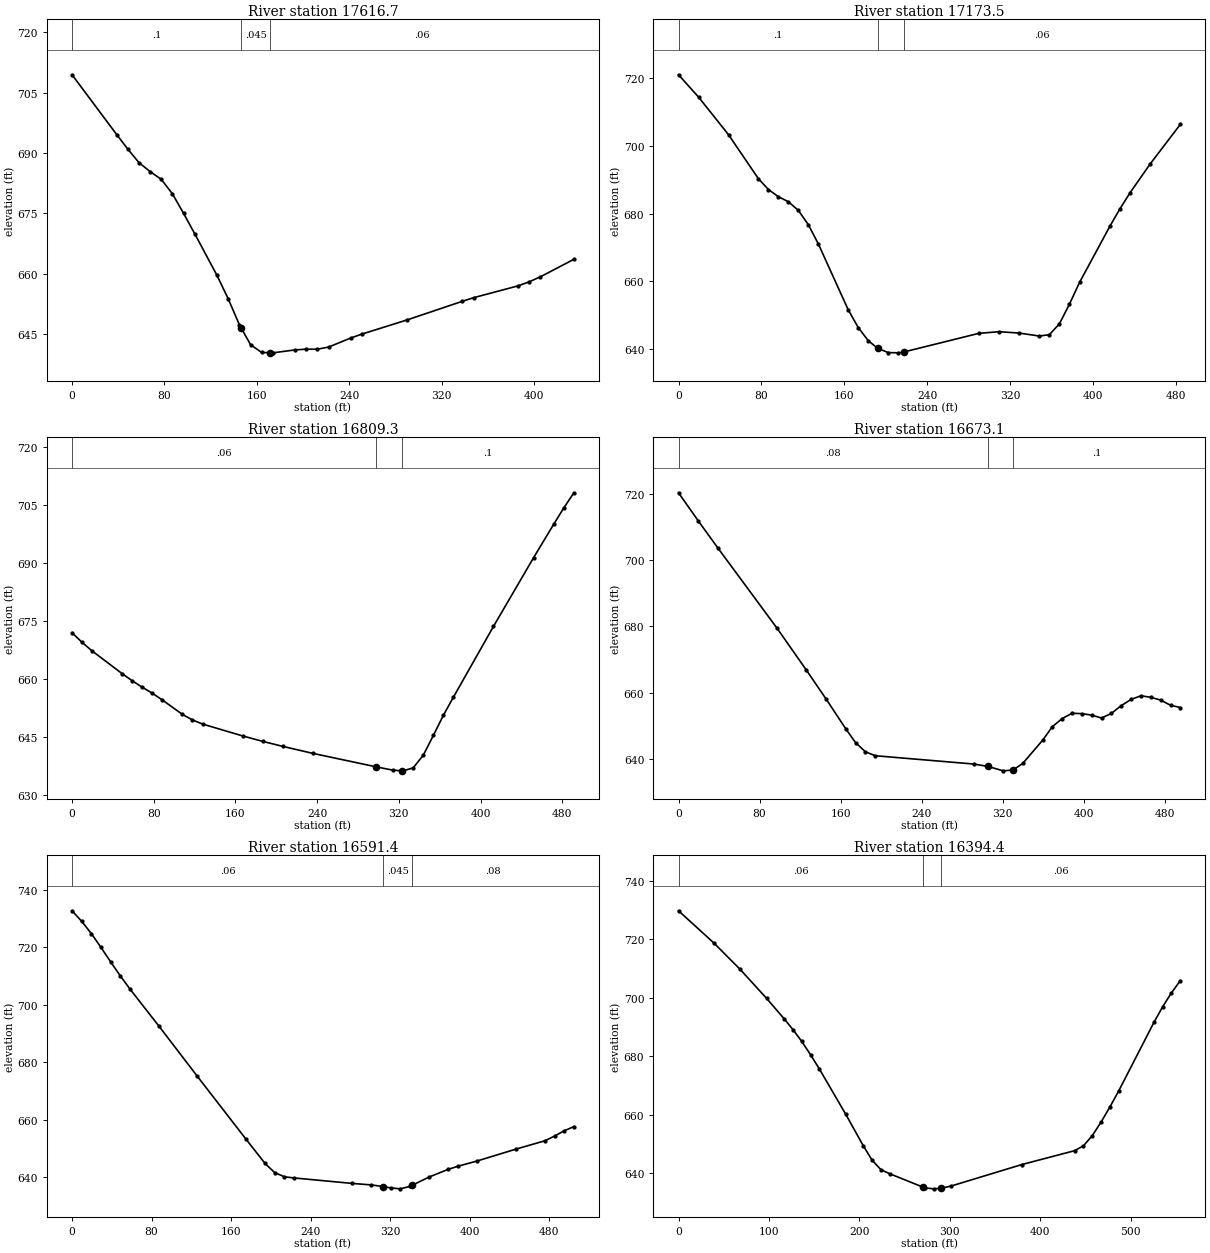
Type RM Length L Ch R = 1 ,17616.7 ,426.7,443.2,457
XS GIS Cut Line= 2
     1665988.372       547222.24     1665554.168      547236.551
#Sta/Elev= 30
       0  709.44    38.6   694.6    48.3  690.96    57.9  687.61    67.6  685.39
    77.2  683.46    86.9  679.85    96.5  675.02   106.2  669.94   125.5  659.57
   135.2  653.76   144.8  647.35   146.5  646.48   154.5  642.38   164.1  640.45
   171.5  640.37   173.8  640.35   193.1  641.08   202.7  641.26   212.4  641.25
     222  641.78   241.4  644.05     251  645.02   289.6  648.49   337.9  653.16
   347.6  654.05   386.2     657   395.8  658.01   405.5  659.25   434.4  663.59
#Mann= 3 , 0 , 0
       0      .1       0   146.5    .045       0   171.5     .06       0
Bank Sta=146.5,171.5
XS Rating Curve= 0 ,0
Exp/Cntr=0.3,0.1

Type RM Length L Ch R = 1 ,17173.5 ,363,364.2,367.1
XS GIS Cut Line= 3
     1666127.886      546919.075     1665947.044      546808.659
     1665703.625      546686.925
#Sta/Elev= 30
       0     721    19.3  714.42    48.2  703.32      77  690.34    86.7  687.13
    96.3  685.01   105.9  683.54   115.6  680.95   125.2  676.74   134.8   671.1
   163.7   651.6   173.4  646.35     183  642.52     192  640.26   202.3     639
   211.9  638.92     217  639.15   289.6  644.67   309.1  645.16   328.5  644.76
     348  643.88   357.7  644.28   367.4   647.5   377.1  653.33   386.8  659.71
     416  676.26   425.7  681.41   435.4  686.12   454.9  694.68     484  706.35
#Mann= 3 , 0 , 0
       0      .1       0     192    .045       0     217     .06       0
Bank Sta=192,217
XS Rating Curve= 0 ,0
Exp/Cntr=0.3,0.1

Type RM Length L Ch R = 1 ,16809.3 ,135.5,136.2,136.8
XS GIS Cut Line= 2
     1666320.155       546644.65     1665912.432      546370.441
#Sta/Elev= 29
       0  671.98     9.8  669.52    19.6   667.3    49.1  661.42      59  659.58
    68.8  657.91    78.6  656.37    88.4  654.63   108.1   650.9   117.9  649.47
   127.8  648.41   167.1  645.34   186.7  643.94   206.4  642.64   235.8  640.84
   297.8  637.36   314.5  636.49   322.8  636.35   324.3  636.33   334.1  637.11
     344  640.39   353.8  645.46   363.6  650.67   373.4  655.33   412.7  673.64
     452   691.4   471.7  700.02   481.5  704.21   491.4  708.14
#Mann= 3 , 0 , 0
       0     .06       0   297.8    .045       0   322.8      .1       0
Bank Sta=297.8,322.8
XS Rating Curve= 0 ,0
Exp/Cntr=0.3,0.1

Type RM Length L Ch R = 1 ,16673.1 ,80.4,81.7,82.9
XS GIS Cut Line= 2
     1666401.121      546544.157     1665996.512      546257.966
#Sta/Elev= 30
       0  720.22    19.4   711.8    38.9  703.59    97.2  679.52   126.3  666.86
   145.8  658.16   165.2  649.21   174.9  645.05   184.6   642.3   194.4  641.12
   291.5  638.63   305.4  637.92   320.7  636.58   330.4  636.83   340.1  638.84
   359.6  645.79   369.3  649.89     379  652.32   388.7   653.9   398.4  653.78
   408.1  653.34   417.8  652.46   427.6  653.88   437.3  656.21     447  658.07
   456.7  659.16   466.4   658.7   476.2  657.87   485.9  656.31   495.6  655.62
#Mann= 3 , 0 , 0
       0     .08       0   305.4    .045       0   330.4      .1       0
Bank Sta=305.4,330.4
XS Rating Curve= 0 ,0
Exp/Cntr=0.3,0.1

Type RM Length L Ch R = 1 ,16591.4 ,199.2,197,194.9
XS GIS Cut Line= 2
     1666449.691      546497.333      1666051.05      546187.364
#Sta/Elev= 30
       0  732.72     9.7  729.04    19.4  724.79    29.1  719.97    38.8  714.96
    48.6  710.03    58.3  705.47    87.4  692.59   126.2  675.06   174.8  653.34
   194.2  644.79   203.9  641.61   213.6  640.15   223.4  639.74   281.6  637.85
     301  637.32   313.3636.7466   320.5  636.28   330.2  635.95   339.9  636.78
   342.5 637.225   359.3  640.06   378.7  642.75   388.4  643.82   407.9  645.67
   446.7  649.77   475.8  652.67   485.6  654.31   495.3  656.17     505   657.6
#Mann= 3 , 0 , 0
       0     .06       0   313.3    .045       0   342.5     .08       0
Bank Sta=313.3,342.5
XS Rating Curve= 0 ,0
Exp/Cntr=0.3,0.1

Type RM Length L Ch R = 1 ,16394.4 ,78.9,67.6,56.3
XS GIS Cut Line= 2
     1666572.729       546329.15     1666114.313       546016.54
#Sta/Elev= 30
       0  729.74    38.9  718.78    68.1  709.73    97.3  699.83   116.8  692.82
   126.6   689.1   136.3  685.07     146  680.52   155.8  675.65     185  660.14
   204.4  649.37   214.2  644.44   223.9  641.22   233.6  639.85   270.6635.2485
   272.6  635.02   282.3   634.7   290.5634.8854   301.8  635.69   379.6     643
     438  647.74   447.8  649.42   457.5  652.87   467.2  657.49     477  662.67
   486.7  668.13   525.7  691.58   535.4  696.96   545.1  701.69   554.9  705.88
#Mann= 3 , 0 , 0
       0     .06       0   270.6    .045       0   290.5     .06       0
Bank Sta=270.6,290.5
XS Rating Curve= 0 ,0
Exp/Cntr=0.3,0.1

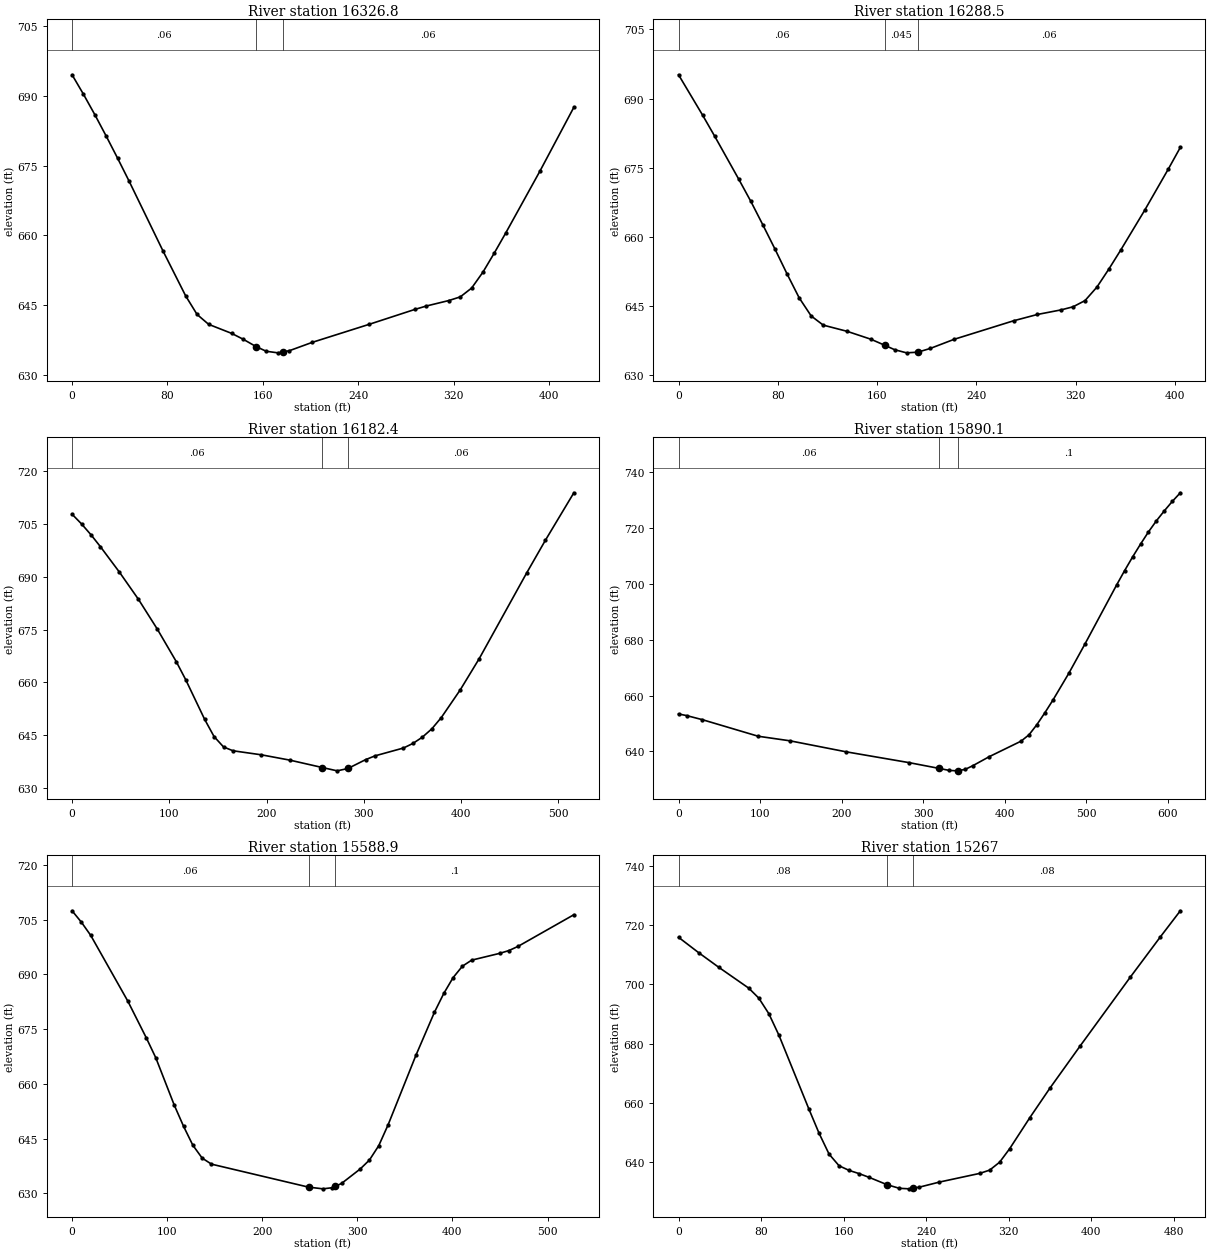
Type RM Length L Ch R = 1 ,16326.8 ,43.5,38.4,40.2
XS GIS Cut Line= 4
      1666538.67      546176.504     1666445.237      546128.981
     1666340.574      546110.157     1666200.747      545954.068
#Sta/Elev= 29
       0  694.45     9.5   690.3    19.1  685.89    28.6  681.31    38.1   676.6
    47.6  671.76    76.2   656.7    95.3  647.02   104.8  643.07   114.5  640.95
   133.8  639.01   143.5  637.75   154.4  636.16   162.8  635.18   172.5  634.84
   176.7635.0422   182.2   635.3   201.5   637.1   249.3  640.97   287.4  644.15
   296.9  644.87     316  646.06   325.5  646.84     335  648.73   344.5  652.15
     354  656.24   363.6  660.54   392.2  673.77   420.7  687.48
#Mann= 3 , 0 , 0
       0     .06       0   154.4    .045       0   176.7     .06       0
Bank Sta=154.4,176.7
XS Rating Curve= 0 ,0
Exp/Cntr=0.3,0.1

Type RM Length L Ch R = 1 ,16288.5 ,90.5,106.1,113.8
XS GIS Cut Line= 4
     1666562.836      546143.103     1666452.296      546081.942
     1666375.856      546081.936     1666226.514      545946.683
#Sta/Elev= 30
       0  695.15    19.4  686.39    29.2  681.79    48.6  672.46    58.3  667.67
      68  662.56    77.7  657.35    87.5  651.92    97.2  646.77   106.9  642.83
   116.6  640.85   135.9   639.5     155  637.79   166.4636.4521   174.1  635.52
   183.7  634.84   192.7 634.982   202.8  635.79     222  637.77   269.9  641.79
   289.1  643.16   308.3  644.16   317.9  644.83   327.5  646.17   337.1   649.1
   346.7     653   356.3  657.14   375.5  665.73   394.7  674.74   404.3   679.4
#Mann= 3 , 0 , 0
       0     .06       0   166.4    .045       0   192.7     .06       0
Bank Sta=166.4,192.7
XS Rating Curve= 0 ,0
Exp/Cntr=0.3,0.1

Type RM Length L Ch R = 1 ,16182.4 ,293.5,292.3,291.6
XS GIS Cut Line= 2
     1666653.552      546107.089     1666197.868      545864.945
#Sta/Elev= 30
       0  707.82     9.7  705.07    19.5  701.95    29.2  698.56    48.7  691.33
    68.2  683.62    87.6  675.14   107.1  665.89   116.8  660.75   136.3  649.45
     146  644.54   155.8  641.57   165.5  640.49   194.7  639.34   223.9  637.83
   257.4635.7197   272.6  634.78   283.7635.4482   301.8  637.96   311.6  639.05
   340.8  641.28   350.5  642.58   360.2  644.36     370  646.75   379.7  649.95
   399.2  657.84   418.7  666.72   467.3  691.02   486.8  700.44     516  713.92
#Mann= 3 , 0 , 0
       0     .06       0   257.4    .045       0   283.7     .06       0
Bank Sta=257.4,283.7
XS Rating Curve= 0 ,0
Exp/Cntr=0.3,0.1

Type RM Length L Ch R = 1 ,15890.1 ,301.7,301.3,298.9
XS GIS Cut Line= 2
     1666783.832      545848.161     1666235.113      545570.274
#Sta/Elev= 30
       0  653.41     9.8  652.84    29.3  651.36    97.6  645.44   136.7   643.8
     205  639.89   283.1  635.97     319633.9554   331.9  633.21   341.7  633.06
   342.7633.1141   351.5  633.59   361.2  634.97   380.8  638.12   419.8  643.67
   429.6  645.95   439.3   649.6   449.1  653.86   458.9  658.36   478.4  667.96
   497.9  678.29     537  699.56   546.7  704.65   556.5  709.55   566.3  714.18
     576  718.54   585.8  722.54   595.6  726.14   605.3  729.48   615.1  732.56
#Mann= 3 , 0 , 0
       0     .06       0     319    .045       0   342.7      .1       0
Bank Sta=319,342.7
XS Rating Curve= 0 ,0
Exp/Cntr=0.3,0.1

Type RM Length L Ch R = 1 ,15588.9 ,322,321.9,312.2
XS GIS Cut Line= 2
      1666904.07      545598.962     1666435.495      545356.174
#Sta/Elev= 30
       0  707.47     9.8  704.34    19.6  700.73    58.6  682.71    78.2  672.56
      88  667.19   107.5  654.16   117.3  648.35     127  643.19   136.8  639.66
   146.6     638   248.7631.6969   263.9  631.23   273.6  631.54   276.5631.8862
   283.4  632.71     303  636.67   312.7  639.12   322.5  643.06   332.3  648.75
   361.6  667.84   381.1  679.66   390.9   684.8   400.7  689.14   410.5  692.28
   420.2  693.93   449.6  695.79   459.3  696.55   469.1  697.72   527.7  706.39
#Mann= 3 , 0 , 0
       0     .06       0   248.7    .045       0   276.5      .1       0
Bank Sta=248.7,276.5
XS Rating Curve= 0 ,0
Exp/Cntr=0.3,0.1

Type RM Length L Ch R = 1 ,15267   ,174.7,175.9,178.1
XS GIS Cut Line= 2
     1666992.256      545313.329     1666540.775      545132.695
#Sta/Elev= 30
       0  715.86    19.4   710.7    38.9  705.77    68.1   698.7    77.8  695.35
    87.5  690.11    97.3  682.84   126.4   657.9   136.2  649.79   145.9  642.75
   155.6  638.82   165.3  637.27   175.1  636.17   184.8  634.91   202.2632.4319
     214  631.23   223.7  631.05   227.4631.2674   233.4  631.62   252.9  633.34
   291.8  636.25   301.5  637.36   311.2  640.04   320.9  644.58   340.4  655.02
   359.8  664.94     389  679.12   437.6  702.32   466.8  715.93   486.3   724.8
#Mann= 3 , 0 , 0
       0     .08       0   202.2    .045       0   227.4     .08       0
Bank Sta=202.2,227.4
XS Rating Curve= 0 ,0
Exp/Cntr=0.3,0.1

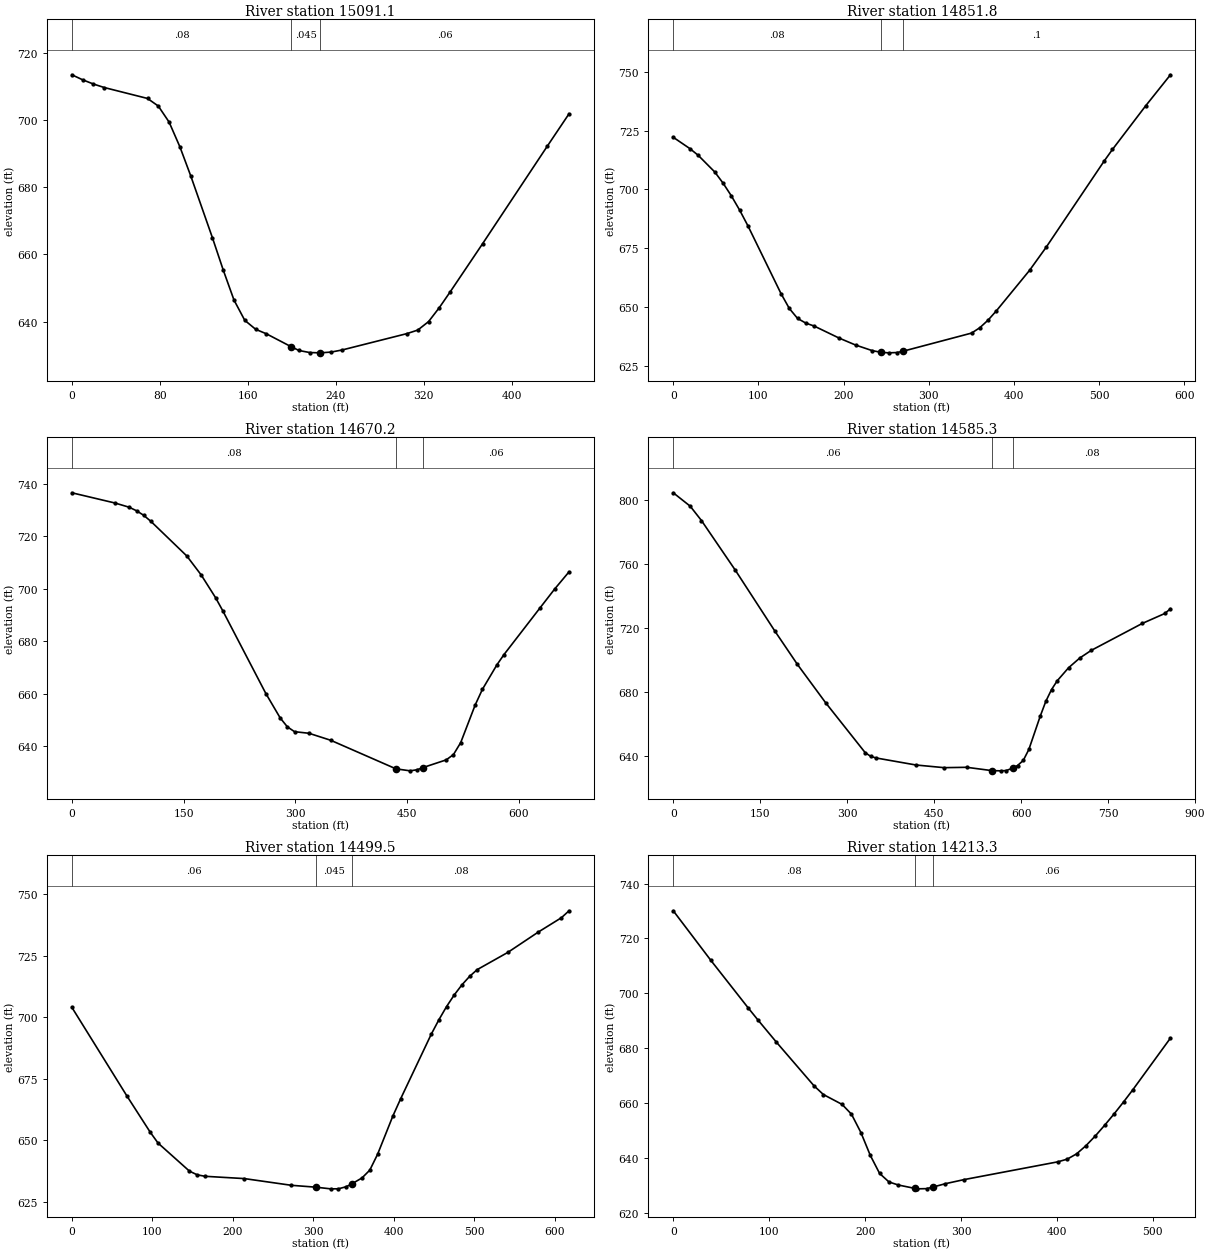
Type RM Length L Ch R = 1 ,15091.1 ,235.6,239.3,224.7
XS GIS Cut Line= 2
      1667033.58       545159.54     1666622.169      544972.234
#Sta/Elev= 30
       0  713.49     9.8     712    19.6  710.74    29.5  709.69    68.8  706.44
    78.6  704.18    88.4  699.42    98.3  691.99   108.1  683.39   127.8  664.99
   137.6   655.4   147.4  646.44   157.2   640.4   167.1  637.73   176.9  636.38
   199.6632.5084   206.5  631.42   216.2  630.81   225.5630.7244     226  630.72
   235.8  630.95   245.7  631.57   304.6  636.44   314.5   637.5   324.3  640.02
   334.1  644.19     344  648.89   373.4   663.2   432.4  692.32     452  701.88
#Mann= 3 , 0 , 0
       0     .08       0   199.6    .045       0   225.5     .06       0
Bank Sta=199.6,225.5
XS Rating Curve= 0 ,0
Exp/Cntr=0.3,0.1

Type RM Length L Ch R = 1 ,14851.8 ,180.4,181.6,181.9
XS GIS Cut Line= 2
     1667110.363      545014.656     1666589.428      544750.665
#Sta/Elev= 30
       0  722.14    19.5  717.35    29.2  714.53    48.7  707.45    58.4  702.75
    68.1  697.38    77.9   691.3    87.6  684.66   126.5  655.88   136.3  649.54
     146  645.31   155.7  643.32   165.5  642.07   194.7  636.99   214.1  634.03
   233.6  631.66   243.9630.9345   253.1  630.71   262.8  630.84   269.4631.3503
   350.4  639.09   360.1  641.37   369.9  644.63   379.6  648.56   418.5   665.7
     438   675.5   506.1  712.05   515.9     717   554.8  735.45     584  748.66
#Mann= 3 , 0 , 0
       0     .08       0   243.9    .045       0   269.4      .1       0
Bank Sta=243.9,269.4
XS Rating Curve= 0 ,0
Exp/Cntr=0.3,0.1

Type RM Length L Ch R = 1 ,14670.2 ,114.5,84.9,72.2
XS GIS Cut Line= 3
      1667154.09      545117.018     1667104.567      544822.219
     1666769.111      544670.015
#Sta/Elev= 30
       0  736.62    57.9  732.72    77.1   731.1    86.8  729.77    96.4  728.05
   106.1  725.73   154.3  712.54   173.6  705.31   192.9  696.65   202.5   691.7
   260.4  660.12   279.6  650.84   289.3  647.42   298.9  645.59   318.3  644.98
   347.4  642.32     435631.4336     454  630.67   463.7   631.1   470.7631.8658
   502.5  634.85   512.2  636.88   521.9  641.43   541.3  655.74     551  661.71
   570.4  671.02     580  674.98   628.5  692.81   647.9  699.91   667.3   706.5
#Mann= 3 , 0 , 0
       0     .08       0     435    .045       0   470.7     .06       0
Bank Sta=435,470.7
XS Rating Curve= 0 ,0
Exp/Cntr=0.3,0.1

Type RM Length L Ch R = 1 ,14585.3 ,84.4,85.8,75.7
XS GIS Cut Line= 3
     1667524.597      544520.298     1666972.845       544679.54
     1666696.492      544617.515
#Sta/Elev= 30
       0   804.2    29.2  795.83    48.7  786.84   107.1  755.82   175.2  717.85
   214.1  697.03   262.8  673.08   330.9  641.96   340.7  639.53   350.4  638.55
   418.5   634.2   467.2  632.53   506.1  632.76   549.1630.7058   564.5  630.55
   574.3  630.73   586.5  632.42   593.8  633.88   603.6  637.02   613.3  643.91
   632.9  664.69   642.6  674.01   652.4  681.31   662.2  686.79   681.7   694.9
   701.2  701.04   720.8  705.76   808.7  722.57   847.7  728.81   857.5  731.76
#Mann= 3 , 0 , 0
       0     .06       0   549.1    .045       0   586.5     .08       0
Bank Sta=549.1,586.5
XS Rating Curve= 0 ,0
Exp/Cntr=0.3,0.1

Type RM Length L Ch R = 1 ,14499.5 ,276.7,286.2,295.2
XS GIS Cut Line= 3
      1667306.49      544499.673     1666942.394       544607.84
     1666710.865      544553.476
#Sta/Elev= 30
       0  704.08    68.2  668.11    97.4  653.24   107.1  648.83   146.1  637.41
   155.8   635.9   165.6  635.31   214.3  634.38   272.7  631.65   303.2630.8817
   321.4  630.21   331.1  630.22   340.9  631.08     348632.2804   360.4  634.64
   370.1  637.82   379.8  644.28   398.8  659.87   408.4  666.84   446.4   693.1
   455.9  698.99   465.4  704.35     475  709.11   484.5   713.2     494  716.64
   503.5  719.41   541.6  726.43   579.6  734.74   608.1  740.53   617.6  743.36
#Mann= 3 , 0 , 0
       0     .06       0   303.2    .045       0     348     .08       0
Bank Sta=303.2,348
XS Rating Curve= 0 ,0
Exp/Cntr=0.3,0.1

Type RM Length L Ch R = 1 ,14213.3 ,334,343.9,386.7
XS GIS Cut Line= 2
     1667330.239      544341.722     1666812.366      544320.995
#Sta/Elev= 30
       0   730.1    39.1  712.06    78.2  694.64      88   690.4   107.6  682.16
   146.7  666.28   156.5  663.09     176  659.49   185.8  655.91   195.6  649.24
   205.4   640.9   215.1  634.32   224.9   631.2   234.7  630.09   252.2628.8372
   254.2   628.7     264  628.77   270.8629.3536   283.6  630.57   303.2  632.07
   400.9  638.55   410.7  639.53   420.5  641.47   430.3  644.47   440.1  648.04
   449.8  651.93   459.6  656.05   469.4  660.38   479.2  664.89   518.3  683.68
#Mann= 3 , 0 , 0
       0     .08       0   252.2    .045       0   270.8     .06       0
Bank Sta=252.2,270.8
XS Rating Curve= 0 ,0
Exp/Cntr=0.3,0.1

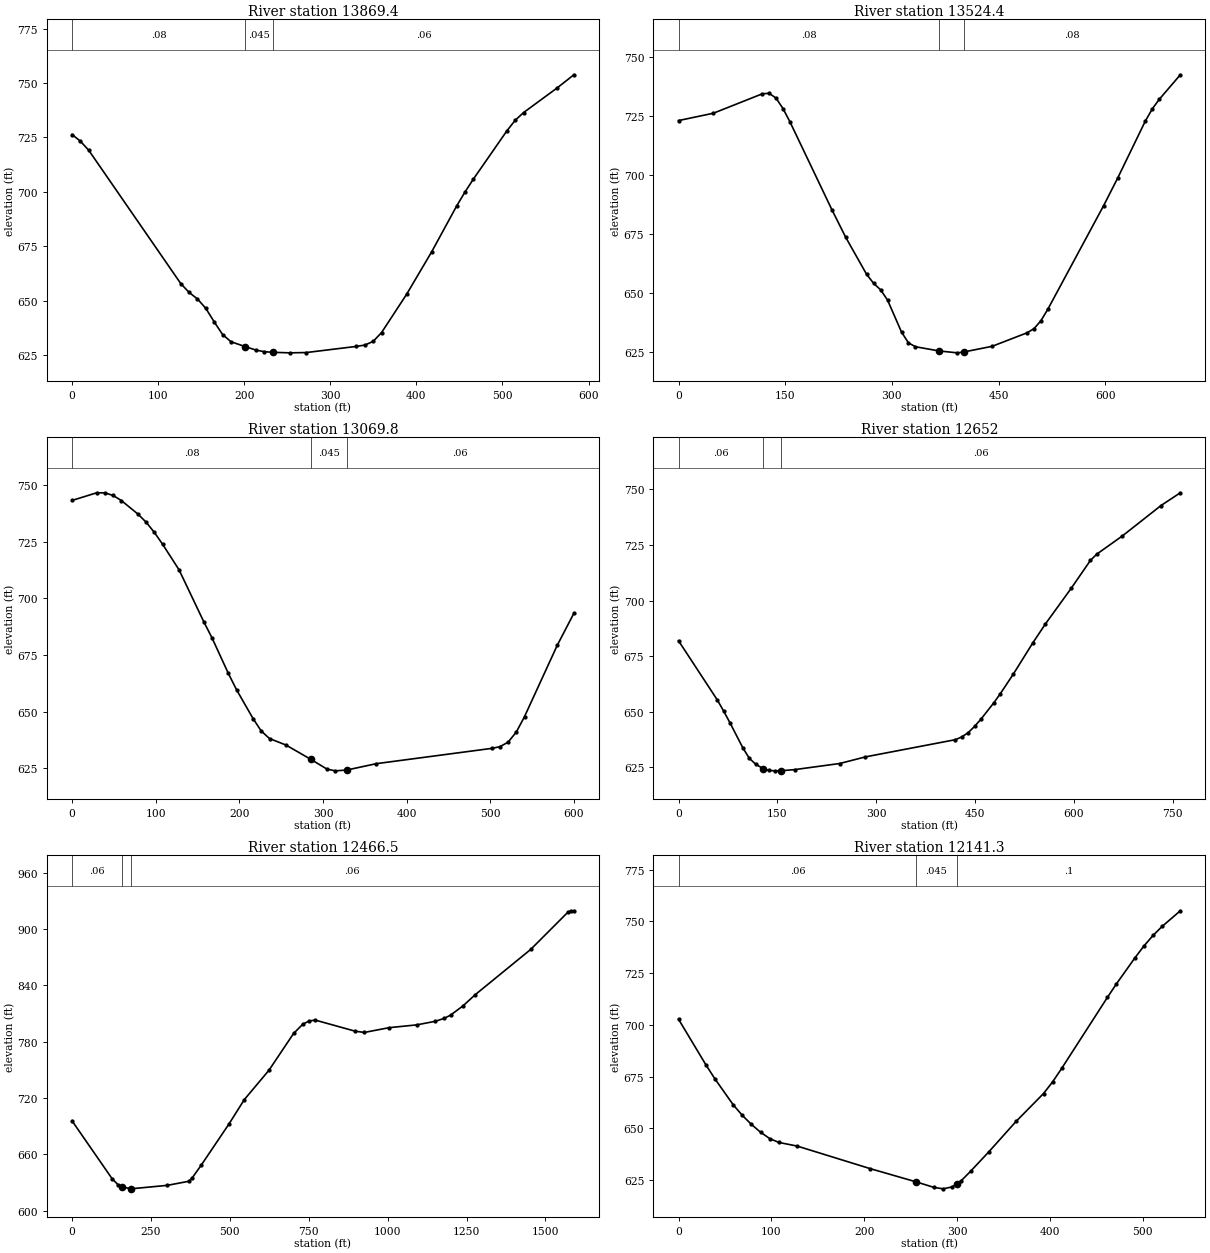
Type RM Length L Ch R = 1 ,13869.4 ,316.3,345,298.5
XS GIS Cut Line= 2
     1667366.531      544124.069     1666836.022      543882.541
#Sta/Elev= 30
       0  726.31     9.7  723.24    19.4  719.06   126.3  657.82     136  653.75
   145.7  650.77   155.4  646.43   165.2  640.18   174.9  634.42   184.6  631.12
   201.1628.8906   213.7  627.28   223.4  626.54   233.5626.2557   252.6  626.02
     272  626.15   330.3  628.98     340  629.58   349.7  631.26   359.5  635.32
   388.6   652.9   417.8  672.48   446.9  693.59   456.6  700.01   466.3  705.91
   505.2  728.06   514.9  732.92   524.6  736.43   563.5  747.72   582.9  753.76
#Mann= 3 , 0 , 0
       0     .08       0   201.1    .045       0   233.5     .06       0
Bank Sta=201.1,233.5
XS Rating Curve= 0 ,0
Exp/Cntr=0.3,0.1

Type RM Length L Ch R = 1 ,13524.4 ,456,454.5,450.1
XS GIS Cut Line= 2
     1667609.948      543882.894     1666929.598      543695.426
#Sta/Elev= 30
       0  723.12      49  726.22   117.6  734.42   127.4  734.67   137.2  732.59
     147  728.16   156.8  722.51   215.6  685.42   235.2  673.65   264.6  657.97
   274.4  654.21   284.2  651.46     294   647.1   313.6  633.57   323.4     629
   333.2  627.38   366.6625.5795   392.1  624.79   401.3625.1655   441.1  627.56
   490.1  633.26   499.9  635.02   509.7   638.4   519.5  643.32   597.9  687.14
   617.5  698.72   656.7  723.04   666.5  728.16   676.3  732.19   705.7   742.5
#Mann= 3 , 0 , 0
       0     .08       0   366.6    .045       0   401.3     .08       0
Bank Sta=366.6,401.3
XS Rating Curve= 0 ,0
Exp/Cntr=0.3,0.1

Type RM Length L Ch R = 1 ,13069.8 ,417.1,417.9,420.2
XS GIS Cut Line= 2
     1667684.302      543458.909     1667102.193      543313.489
#Sta/Elev= 30
       0  743.12    29.5   746.5    39.3  746.46    49.2   745.3      59  743.06
    78.7  737.12    88.5  733.55    98.4  729.02   108.2  723.82   127.9  712.53
   157.4  689.66   167.2  682.59   186.9  666.77   196.7  659.58   216.4  646.88
   226.2   641.4   236.1  638.05   255.7  635.22   285.5628.8852   304.9  624.56
   314.8  623.82   328.2624.1596   363.9  626.99   501.6  633.72   511.5  634.46
   521.3  636.45   531.2  640.94     541  647.74   580.3  679.33     600  693.31
#Mann= 3 , 0 , 0
       0     .08       0   285.5    .045       0   328.2     .06       0
Bank Sta=285.5,328.2
XS Rating Curve= 0 ,0
Exp/Cntr=0.3,0.1

Type RM Length L Ch R = 1 ,12652   ,167.2,185.5,203.6
XS GIS Cut Line= 3
     1667506.701      543011.745     1667225.279      542976.516
      1666793.18      543180.647
#Sta/Elev= 30
       0  681.92    58.7  655.39    68.5  650.32    78.2  644.98    97.8  633.68
   107.6  629.04   117.4  626.37   128.2624.4924   136.9  623.64   146.7  623.46
   154.8623.4836     176     624   244.5  626.75   283.6  629.73   420.2  637.47
   429.9  638.71   439.7  640.65   449.4  643.48   459.2  646.78   478.7  654.13
   488.4  658.17   507.9  666.86   537.2  680.77   556.7  689.46   595.7  705.42
     625  718.02   634.7  720.86   673.7  729.07   732.2  742.71   761.5  748.44
#Mann= 3 , 0 , 0
       0     .06       0   128.2    .045       0   154.8     .06       0
Bank Sta=128.2,154.8
XS Rating Curve= 0 ,0
Exp/Cntr=0.3,0.1

Type RM Length L Ch R = 1 ,12466.5 ,325.9,325.2,325
XS GIS Cut Line= 3
     1667575.332      542958.794     1666959.306      542361.991
     1666320.623       542003.88
#Sta/Elev= 30
       0  695.63   126.7  634.06   146.2  627.36   159.5625.4651   185.2   623.2
   185.7623.2062   302.2  626.93   370.4  631.31   380.1  634.62   409.4  648.52
   497.1  692.28   545.8  718.32   623.8  749.56   701.8  788.76     731  798.64
   750.5     802     770  803.07   896.8  791.23     926  789.87  1004.2  794.94
    1092  797.93  1150.6  801.74  1179.9  804.94  1199.4  808.37  1238.5  818.14
  1277.5  830.13  1453.2  878.36  1570.4   917.8  1580.2  919.53  1589.9  918.87
#Mann= 3 , 0 , 0
       0     .06       0   159.5    .045       0   185.7     .06       0
Bank Sta=159.5,185.7
XS Rating Curve= 0 ,0
Exp/Cntr=0.3,0.1

Type RM Length L Ch R = 1 ,12141.3 ,261.1,256.9,251.4
XS GIS Cut Line= 2
      1667763.47      542750.283     1667367.572      542382.111
#Sta/Elev= 30
       0  702.76    29.5  680.73    39.3  673.89      59  661.38    68.8  656.29
    78.6  651.92    88.5  648.15    98.3   645.1   108.1  643.24   127.8   641.5
   206.4  630.61   256.2 624.178   275.2  621.53   285.1  620.84   294.9  621.81
   299.5623.2228   304.7  624.82   314.6  629.31   334.2  638.67   363.7  653.44
   393.2  666.86     403  672.51   412.8  679.03     462  713.28   471.8  719.87
   491.5   732.3   501.3   738.1   511.2  743.24     521   747.6   540.6  755.15
#Mann= 3 , 0 , 0
       0     .06       0   256.2    .045       0   299.5      .1       0
Bank Sta=256.2,299.5
XS Rating Curve= 0 ,0
Exp/Cntr=0.3,0.1

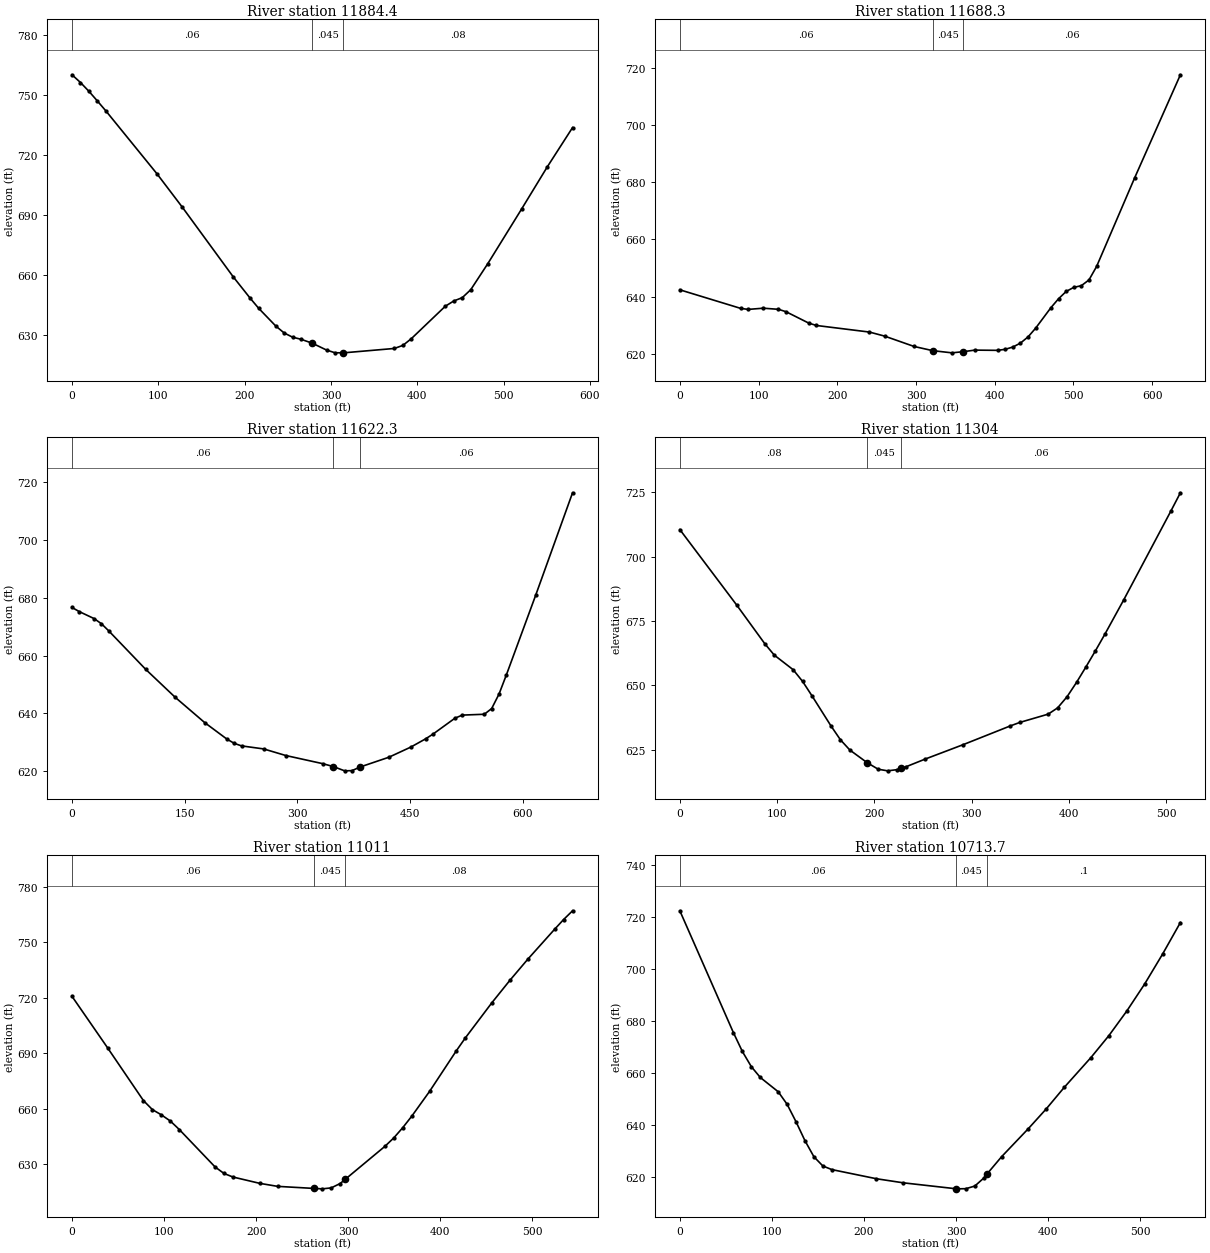
Type RM Length L Ch R = 1 ,11884.4 ,212.1,196.1,180.1
XS GIS Cut Line= 2
     1668024.491      542586.902       1667532.5      542280.079
#Sta/Elev= 30
       0  759.87     9.8  756.01    19.7  751.56    29.5  746.72    39.3  741.78
    98.3  710.44   127.8  693.67   186.7   658.9   206.4  648.18   216.2  643.15
   235.9  634.34   245.7  630.82   255.5   628.7   265.3  627.66   278.5625.6634
   294.8  622.28   304.6  620.92   314.1620.8816   314.5  620.88   373.4  623.07
   383.3  624.61   393.1  627.98   432.4  644.18   442.2   646.8   452.1  648.48
   461.9  652.46   481.6  665.44   520.9  692.85   550.3  713.68   579.8  733.48
#Mann= 3 , 0 , 0
       0     .06       0   278.5    .045       0   314.1     .08       0
Bank Sta=278.5,314.1
XS Rating Curve= 0 ,0
Exp/Cntr=0.3,0.1

Type RM Length L Ch R = 1 ,11688.3 ,66,66,66
XS GIS Cut Line= 4
     1668175.385      542378.204     1667930.108       542291.36
      1667894.69      542260.941     1667565.867      542266.585
#Sta/Elev= 30
       0  642.44    77.1  635.97    86.7   635.6     106  636.02   125.3  635.63
   134.9  634.79   163.8  630.81   173.5  629.99   240.9  627.69   260.2  626.27
   297.6  622.66   321.2621.2012   345.6  620.44   359.9620.8384   374.6  621.39
   403.6  621.31   413.3  621.67     423  622.47   432.6  623.83   442.3     626
     452  629.07   471.3  636.19     481  639.31   490.7  641.86   500.3  643.28
     510  643.88   519.7  645.89   529.4   650.6   577.7  681.51   635.8  717.49
#Mann= 3 , 0 , 0
       0     .06       0   321.2    .045       0   359.9     .06       0
Bank Sta=321.2,359.9
XS Rating Curve= 0 ,0
Exp/Cntr=0.3,0.1

Type RM Length L Ch R = 1 ,11622.3 ,327.3,318.3,309.5
XS GIS Cut Line= 3
     1668214.463      542297.893     1667907.374      542195.081
     1667564.741      542200.963
#Sta/Elev= 30
       0  676.57     9.8  675.13    29.4  672.74    39.2  670.96    49.1  668.45
    98.1  655.23   137.4  645.58   176.6  636.87   206.1  631.19   215.9  629.71
   225.7  628.82   255.2  627.77   284.6   625.5   333.6   622.7   347.9621.6918
     363  620.21   372.8  620.28   383.6621.5339   421.8  624.89   451.1   628.4
   470.7  631.23   480.5  632.85   509.9  638.37   519.7  639.44     549  639.73
   558.8   641.7   568.6   646.7   578.4  653.32   617.6  680.93   666.5  716.14
#Mann= 3 , 0 , 0
       0     .06       0   347.9    .045       0   383.6     .06       0
Bank Sta=347.9,383.6
XS Rating Curve= 0 ,0
Exp/Cntr=0.3,0.1

Type RM Length L Ch R = 1 ,11304   ,292.6,293,293.3
XS GIS Cut Line= 2
      1667984.12      541826.808     1667497.577      541994.439
#Sta/Elev= 30
       0  710.52    58.3  681.26    87.4  666.12    97.1  661.72   116.5  656.05
   126.2   651.5   135.9  645.87   155.4  634.19   165.1  628.81   174.8  624.82
   192.5619.9344   203.9  617.37   213.6  616.74   223.3   617.2   227.1617.6701
     233   618.4   252.4  621.34   291.3  626.92   339.8  634.21   349.6  635.57
   378.7  638.78   388.4  641.22   398.1  645.55   407.8   651.1   417.5  657.13
   427.2  663.36   436.9   669.8   456.4  683.23   504.9  717.77   514.6  724.82
#Mann= 3 , 0 , 0
       0     .08       0   192.5    .045       0   227.1     .06       0
Bank Sta=192.5,227.1
XS Rating Curve= 0 ,0
Exp/Cntr=0.3,0.1

Type RM Length L Ch R = 1 ,11011   ,285.1,297.3,307.5
XS GIS Cut Line= 2
     1667875.775      541594.593       1667359.4      541764.104
#Sta/Elev= 30
       0  720.67    38.8  692.75    77.6  664.35    87.4  659.46      97  656.69
   106.8  653.32   116.5  648.75   155.3  628.56     165  625.02   174.7   623.1
   203.8  619.68   223.2  618.05   262.7616.9325   271.7  616.71   281.4  617.21
   291.2  619.59   296.7621.8637   339.7  639.64   349.4  644.22   359.1  649.74
   368.8  655.88   388.2  669.31   417.3  691.27     427  698.17   456.1  717.35
   475.6  729.41     495  740.79   524.1  756.95   533.8  762.17   543.5  766.89
#Mann= 3 , 0 , 0
       0     .06       0   262.7    .045       0   296.7     .08       0
Bank Sta=262.7,296.7
XS Rating Curve= 0 ,0
Exp/Cntr=0.3,0.1

Type RM Length L Ch R = 1 ,10713.7 ,253.2,257.8,263.8
XS GIS Cut Line= 2
     1667833.341      541430.852     1667290.736      541399.935
#Sta/Elev= 30
       0  722.47    58.2  675.48    67.9  668.24    77.6  662.41    87.4  658.22
   106.8  652.73   116.5  647.88   126.2  641.13   135.9  633.84   145.6  627.66
   155.3  624.12     165  622.73   213.5   619.2   242.6  617.63   299.4615.3579
   300.9  615.31   310.6  615.37   320.3  616.39     330  619.46   333.4620.9777
   349.4  627.71   378.5  638.54   397.9  646.14   417.3  654.38   446.4  665.92
   465.8  674.33   485.2  683.78   504.7  694.25   524.1  705.74   543.5  717.94
#Mann= 3 , 0 , 0
       0     .06       0   299.4    .045       0   333.4      .1       0
Bank Sta=299.4,333.4
XS Rating Curve= 0 ,0
Exp/Cntr=0.3,0.1

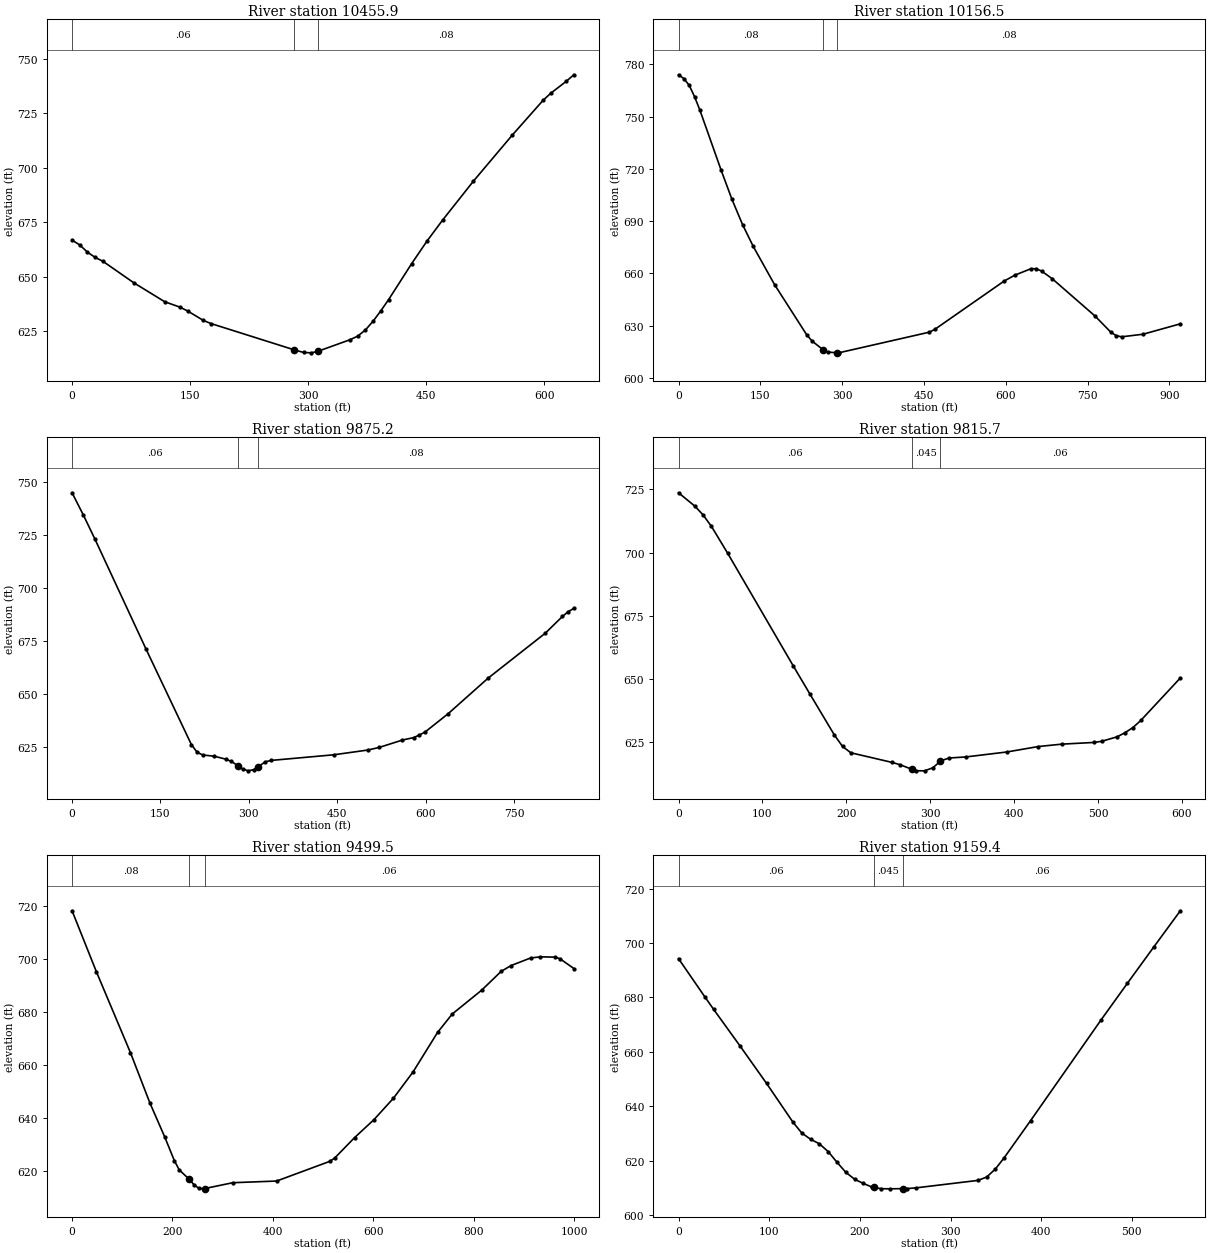
Type RM Length L Ch R = 1 ,10455.9 ,299.3,299.4,299.4
XS GIS Cut Line= 2
     1667899.757      541251.091     1667284.009      541086.474
#Sta/Elev= 30
       0  666.77     9.8  664.51    19.6   661.2    29.4   658.8    39.2  657.01
    78.4  647.14   117.7  638.41   137.3   635.9   147.1   634.1   166.7  629.84
   176.5  628.38   282.3616.2836   294.2  615.08     304  614.92   312.3615.6312
     353  620.94   362.8   622.6   372.6  625.43   382.4  629.48   392.2  634.23
     402  639.35   431.4  655.96   451.1  666.45   470.7  675.98   509.9  693.91
   558.9  714.93   598.2     731     608  734.28   627.6  739.75   637.4  742.79
#Mann= 3 , 0 , 0
       0     .06       0   282.3    .045       0   312.3     .08       0
Bank Sta=282.3,312.3
XS Rating Curve= 0 ,0
Exp/Cntr=0.3,0.1

Type RM Length L Ch R = 1 ,10156.5 ,265,281.2,297.3
XS GIS Cut Line= 2
     1667997.421       540986.72     1667109.033      540747.581
#Sta/Elev= 30
       0  773.96     9.8  771.76    19.6  767.89    29.4  761.38    39.2  753.64
    78.3  719.04    97.9  702.51   117.4  687.99     137  675.45   176.2  653.48
   234.9   624.8   244.7  621.22   264.5616.3094     274  614.85     291614.4233
   293.6  614.41     460  626.28   469.8  627.86     597   655.6   616.6  658.98
     646  662.66   655.8  662.66   665.5  661.35   685.1  656.95   763.4  635.59
   792.8   626.2   802.6  624.25   812.4  623.61   851.5  625.08     920  631.05
#Mann= 3 , 0 , 0
       0     .08       0   264.5    .045       0     291     .08       0
Bank Sta=264.5,291
XS Rating Curve= 0 ,0
Exp/Cntr=0.3,0.1

Type RM Length L Ch R = 1 ,9875.2  ,59.7,59.5,59.5
XS GIS Cut Line= 3
     1668019.518      540877.627     1667744.432      540593.848
     1667358.378      540351.198
#Sta/Elev= 30
       0  744.71    19.3  734.15    38.6  723.01   125.3   671.2   202.4  626.14
   212.1  622.52   221.7  621.24     241  620.66   260.3   619.3   269.9  618.25
   281.7616.1244   289.2  614.64   298.8  613.77   308.5  614.38   315.4615.6733
   327.8  618.01   337.4  618.67   443.7  621.32   501.9  623.57   521.4  624.83
   560.2  628.25   579.6  629.44   589.3  630.65     599   632.1   637.8  640.64
   705.7  657.41   802.7  678.58   831.8  686.46   841.5  688.69   851.2   690.3
#Mann= 3 , 0 , 0
       0     .06       0   281.7    .045       0   315.4     .08       0
Bank Sta=281.7,315.4
XS Rating Curve= 0 ,0
Exp/Cntr=0.3,0.1

Type RM Length L Ch R = 1 ,9815.7  ,335.5,316.2,295.4
XS GIS Cut Line= 3
     1668061.416       540835.43      1667782.48       540547.68
     1667623.448      540431.038
#Sta/Elev= 30
       0  723.63    19.6  718.31    29.3  714.86    39.1  710.41    58.6  699.71
   136.8  655.17   156.4   644.2   185.7  627.92   195.5  623.38   205.3  620.89
   254.1  617.11   263.9  616.19     278614.3793   283.5  613.79   293.2  613.75
     303  614.95   311.8617.4641   312.8  617.75   322.6  618.83   342.1  619.23
     391  621.19   428.9  623.36   457.1  624.31   494.7  624.96   504.1  625.41
   522.8  627.21   532.2  628.84   541.6  630.87     551   633.7     598  650.44
#Mann= 3 , 0 , 0
       0     .06       0     278    .045       0   311.8     .06       0
Bank Sta=278,311.8
XS Rating Curve= 0 ,0
Exp/Cntr=0.3,0.1

Type RM Length L Ch R = 1 ,9499.5  ,339.7,340.1,339.6
XS GIS Cut Line= 4
      1668329.41       540483.87     1667696.343      540387.342
       1667358.6      540335.843     1667341.009      540333.161
#Sta/Elev= 30
       0  718.36    48.5  695.27   116.4  664.63   155.2  645.57   184.4  632.87
   203.8  623.79   213.5  620.31   233.3616.7733   242.6  614.76   252.1  613.38
     262  613.13   264.6613.2507   320.2  615.45   407.5  616.08   514.2  623.58
     524  624.92   562.8   632.5   601.6  639.33   640.4  647.44   679.4  657.37
   728.2  672.31   757.5   679.3   816.1  688.31   855.1  695.45   874.7  697.63
   913.7   700.5   933.2  700.93   962.5  700.82   972.3  700.18   999.8  696.51
#Mann= 3 , 0 , 0
       0     .08       0   233.3    .045       0   264.6     .06       0
Bank Sta=233.3,264.6
XS Rating Curve= 0 ,0
Exp/Cntr=0.3,0.1

Type RM Length L Ch R = 1 ,9159.4  ,283.4,283.2,283.3
XS GIS Cut Line= 2
     1668315.817       540198.03     1667769.982      540106.244
#Sta/Elev= 30
       0  694.27    29.1  680.18    38.8  675.57      68  662.08    97.1  648.38
   126.2  634.13     136  630.11   145.7  627.83   155.4  626.16   165.1  623.28
   174.8  619.38   184.5  615.68   194.2  613.14   203.9  611.57   213.6  610.22
   215.3 610.122   223.3  609.66     233   609.6   247.2609.6836   252.5   609.7
   262.2  609.97   330.2   612.7   339.9  613.94   349.6  616.93   359.3  621.08
   388.4  634.72   466.1  671.75   495.2  685.25   524.4  698.65   553.5  711.88
#Mann= 3 , 0 , 0
       0     .06       0   215.3    .045       0   247.2     .06       0
Bank Sta=215.3,247.2
XS Rating Curve= 0 ,0
Exp/Cntr=0.3,0.1