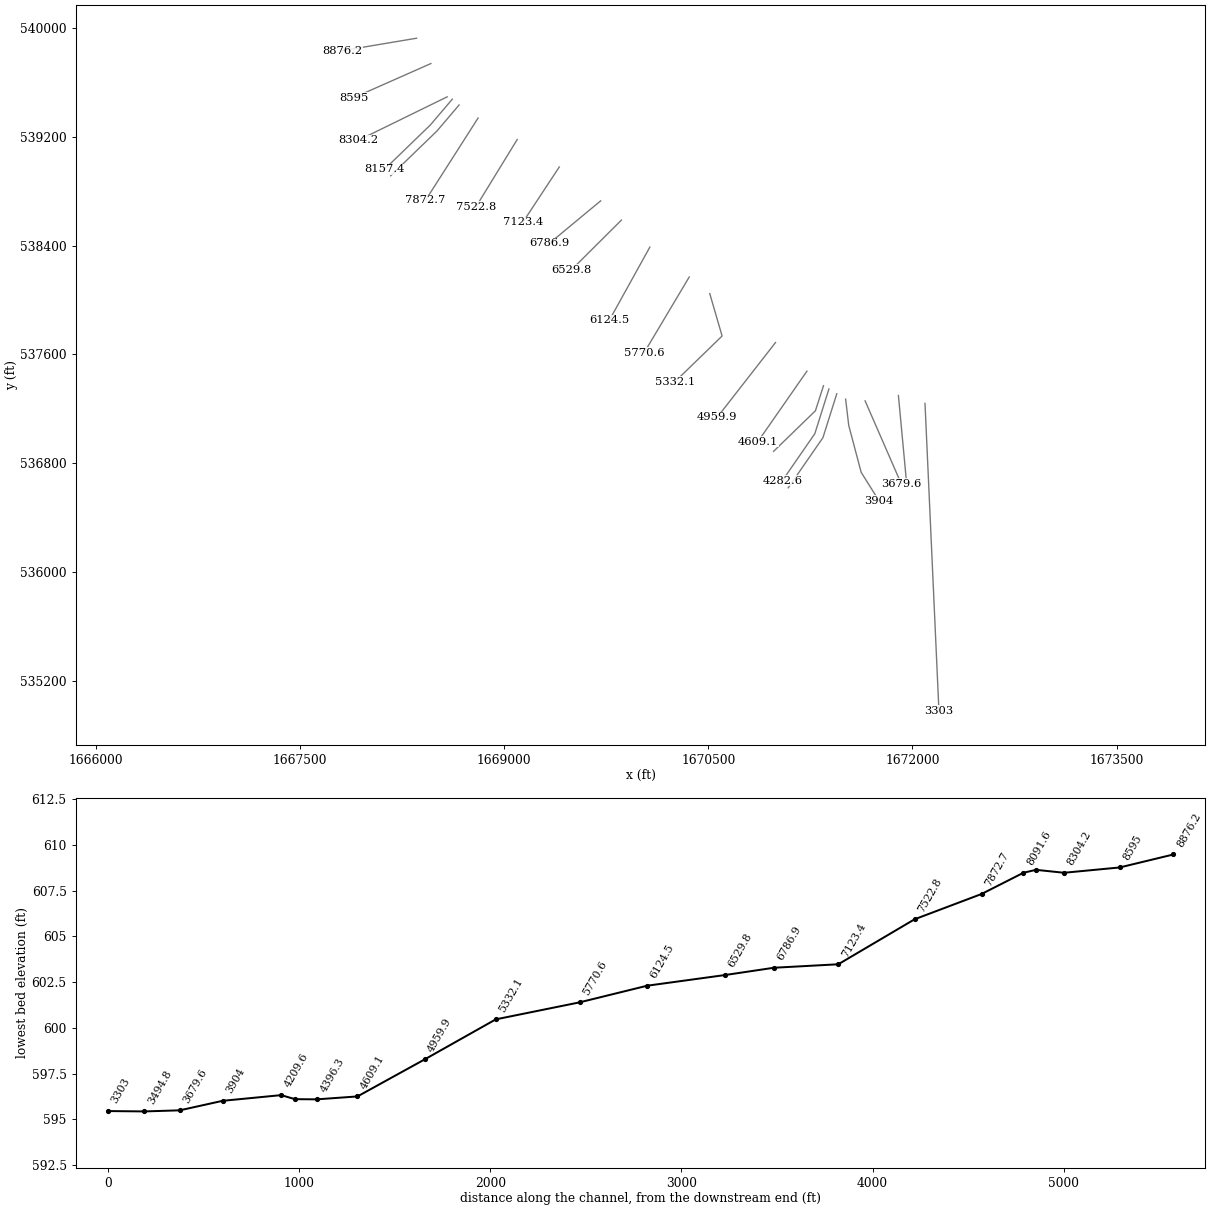
HEC-RAS study NP13.prj: NP13

--- NP13.g01 (geometry) --- (continued)

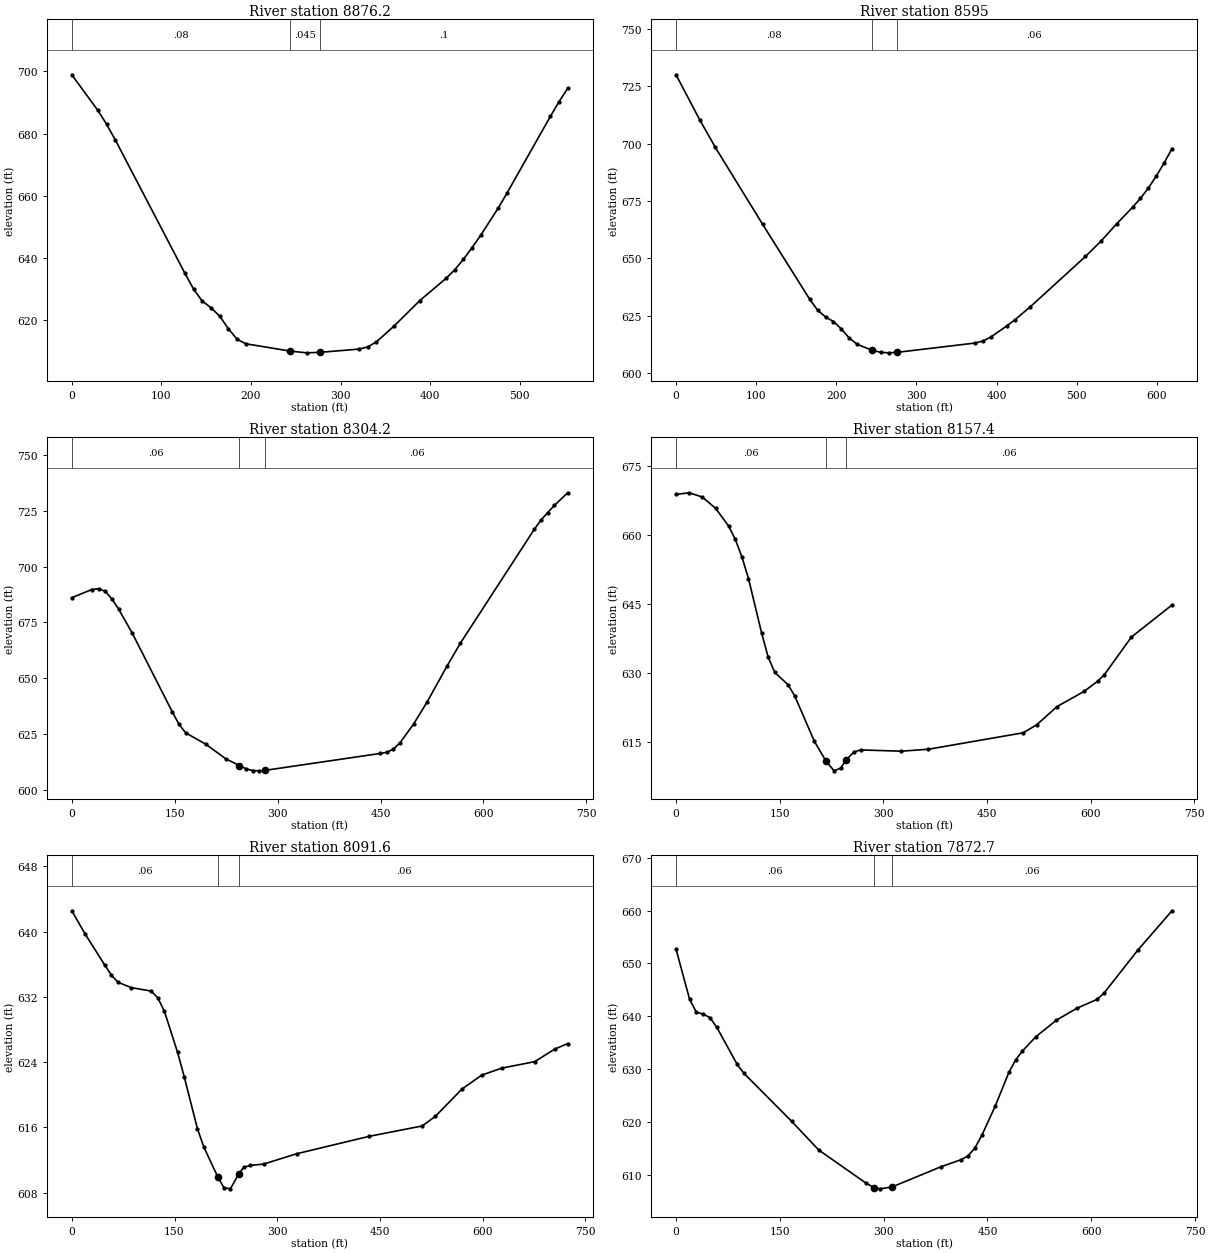
Type RM Length L Ch R = 1 ,8876.2  ,273.9,281.2,288.4
XS GIS Cut Line= 2
     1668357.514      539927.136     1667811.679       539835.35
#Sta/Elev= 30
       0  698.88    29.1  687.43    38.8  682.99    48.6  677.92   126.2  635.09
     136  629.92   145.7  626.09   155.4  623.99   165.1  621.26   174.8  617.21
   184.5  613.84   194.2   612.4   243.3610.0569   262.2  609.48   276.8609.6409
   320.4  610.68   330.2  611.37   339.9  612.99   359.3  617.99   388.4  626.28
   417.6   633.4   427.3  636.15     437  639.52   446.7   643.3   456.4   647.3
   475.8  655.98   485.5  660.73   534.1  685.49   543.8  690.23   553.5  694.54
#Mann= 3 , 0 , 0
       0     .08       0   243.3    .045       0   276.8      .1       0
Bank Sta=243.3,276.8
XS Rating Curve= 0 ,0
Exp/Cntr=0.3,0.1

Type RM Length L Ch R = 1 ,8595    ,289.8,290.8,291
XS GIS Cut Line= 2
     1668462.658      539740.705     1667896.749      539489.793
#Sta/Elev= 30
       0  729.98    29.5   710.4    49.1   698.3   108.1   664.8     167  632.03
   176.9  627.28   186.7   624.4   196.5  622.42   206.4  619.15   216.2  615.23
     226  612.49   244.6609.9174   255.5     609   265.3  608.77   275.4608.9625
   373.4  613.05   383.2  613.96     393  615.68   412.7  620.47   422.5  623.05
   442.2  628.85     511  650.77   530.6  657.54   550.3  665.13   569.9  672.26
   579.7  676.14   589.6  680.63   599.4  685.83   609.2  691.56     619  697.76
#Mann= 3 , 0 , 0
       0     .08       0   244.6    .045       0   275.4     .06       0
Bank Sta=244.6,275.4
XS Rating Curve= 0 ,0
Exp/Cntr=0.3,0.1

Type RM Length L Ch R = 1 ,8304.2  ,134.7,146.8,159.1
XS GIS Cut Line= 2
     1668582.191      539495.709     1667933.219      539177.509
#Sta/Elev= 30
       0  686.05    29.3  689.71    39.1  690.09    48.8  688.89    58.6   685.4
    68.4  680.87    87.9   670.3   146.5  634.89   156.3   629.3     166  625.49
   195.4   620.4   224.6  613.84   244.4610.8398     254  609.39   263.7   608.6
   273.5  608.48   281.9608.7051   449.3  616.26   459.1  616.76   468.8  618.21
   478.6  621.15   498.1  629.41   517.7  639.24     547  655.48   566.5  665.75
     674  716.65   683.7  720.75   693.5  724.14   703.2  727.36   722.8  733.04
#Mann= 3 , 0 , 0
       0     .06       0   244.4    .045       0   281.9     .06       0
Bank Sta=244.4,281.9
XS Rating Curve= 0 ,0
Exp/Cntr=0.3,0.1

Type RM Length L Ch R = 1 ,8157.4  ,65.6,65.8,66
XS GIS Cut Line= 3
      1668619.77      539478.269     1668459.318      539289.321
     1668121.864      538962.201
#Sta/Elev= 30
       0  668.88    19.1  669.23    38.1   668.3    57.2  665.85    76.3  661.95
    85.8  659.09    95.3  655.28   104.9  650.54   123.9  638.67   133.5  633.36
     143  630.08   162.1   627.4   171.6  625.04   200.2  615.09     217610.7873
   228.8  608.64   238.4  609.24   246.1 611.007   257.7  612.76   267.5   613.2
   326.2  612.92   365.4  613.35   502.5  616.93     522  618.66   551.4  622.63
   590.6  625.95   610.2  628.15     620  629.59   659.1  637.78   717.9  644.78
#Mann= 3 , 0 , 0
       0     .06       0     217    .045       0   246.1     .06       0
Bank Sta=217,246.1
XS Rating Curve= 0 ,0
Exp/Cntr=0.3,0.1

Type RM Length L Ch R = 1 ,8091.6  ,213.5,219,225
XS GIS Cut Line= 3
     1668669.798      539435.786     1668507.286      539244.411
     1668167.546      538915.076
#Sta/Elev= 30
       0  642.56    19.3  639.74    48.3  635.89    57.9  634.66    67.6  633.79
    86.9  633.14   115.9  632.72   125.5   631.9   135.2  630.26   154.5   625.2
   164.2  622.22   183.5  615.84   193.1  613.55   213.1609.9567   222.1  608.63
   231.6  608.48   244.2610.3588   251.1  611.12   260.7  611.35     280  611.51
   328.3  612.78   434.5  614.92   511.8  616.19   531.1  617.38   569.7  620.71
   598.7  622.42   627.7  623.27     676  624.07   704.9  625.59   724.2  626.29
#Mann= 3 , 0 , 0
       0     .06       0   213.1    .045       0   244.2     .06       0
Bank Sta=213.1,244.2
XS Rating Curve= 0 ,0
Exp/Cntr=0.3,0.1

Type RM Length L Ch R = 1 ,7872.7  ,350,349.8,348.5
XS GIS Cut Line= 2
      1668809.33      539339.715       1668424.1      538735.443
#Sta/Elev= 30
       0  652.72    19.6  643.23    29.4  640.76    39.3  640.42    49.1  639.73
    58.9  637.91    88.4  630.88    98.2  629.19   166.9  620.13   206.2  614.67
   274.9  608.37   285.9607.5652   294.5  607.32   311.5 607.646   382.8   611.5
   412.3  612.86   422.1  613.58   431.9  615.08   441.8  617.43   461.4  623.05
     481  629.39   490.8  631.75   500.6  633.44   520.3  636.17   549.7  639.27
   579.2  641.52   608.6  643.21   618.4  644.39   667.5  652.57   716.6  659.98
#Mann= 3 , 0 , 0
       0     .06       0   285.9    .045       0   311.5     .06       0
Bank Sta=285.9,311.5
XS Rating Curve= 0 ,0
Exp/Cntr=0.3,0.1

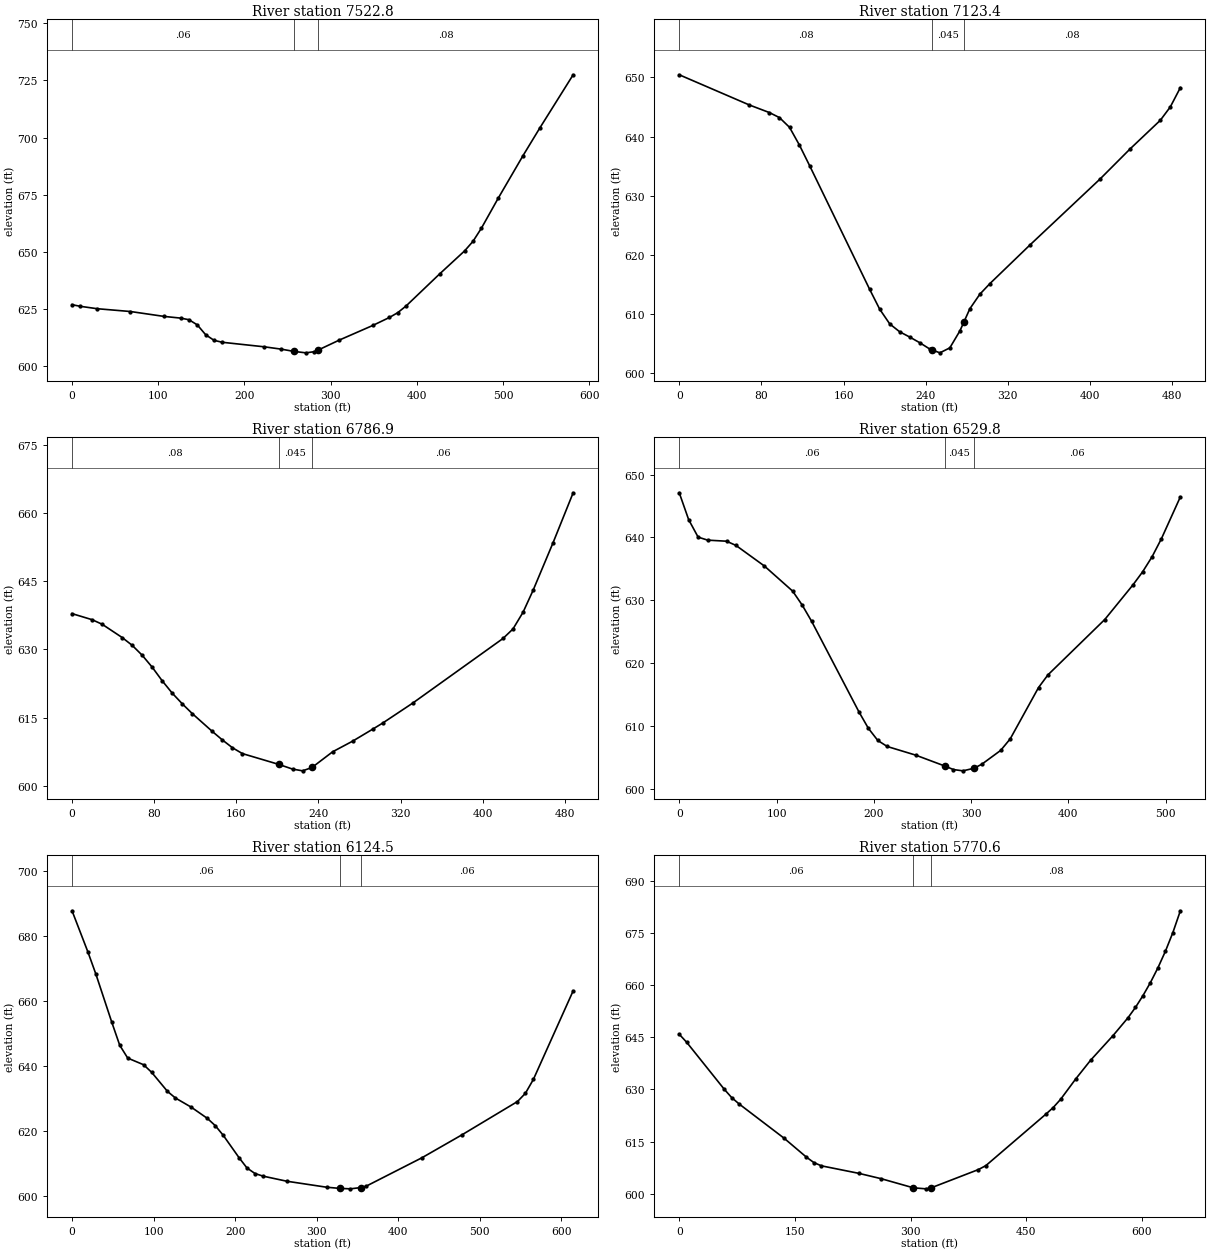
Type RM Length L Ch R = 1 ,7522.8  ,401.8,399.4,397.2
XS GIS Cut Line= 2
     1669096.463      539181.324     1668793.201      538685.466
#Sta/Elev= 30
       0  626.98     9.7  626.27    29.1  625.23    67.8     624   106.6  621.87
   125.9  621.12   135.6  620.42   145.3  618.15     155  613.85   164.7   611.4
   174.4  610.55   222.8  608.58   242.2  607.58   257.4606.5645   271.2  605.94
   280.9  606.44   285.8 607.223     310  611.52   348.8  617.91   368.1   621.4
   377.8  623.51   387.5  626.45   426.2  640.38   455.3   650.5     465  654.66
   474.7  660.36   494.1  673.41   523.1  692.17   542.5   704.2   581.2  727.48
#Mann= 3 , 0 , 0
       0     .06       0   257.4    .045       0   285.8     .08       0
Bank Sta=257.4,285.8
XS Rating Curve= 0 ,0
Exp/Cntr=0.3,0.1

Type RM Length L Ch R = 1 ,7123.4  ,344.9,336.6,328
XS GIS Cut Line= 2
     1669405.738      538979.605     1669137.724      538571.786
#Sta/Elev= 28
       0  650.42    68.3  645.32    87.8  644.04    97.6  643.19   107.4  641.55
   117.1  638.53   126.9   635.1   185.4  614.21   195.2  610.85     205  608.36
   214.7  607.03   224.5  606.14   234.2  605.19     244  604.12   245.7604.0096
   253.8  603.48   263.5  604.32   273.3  607.18   277.2608.6837     283  610.92
   292.8  613.39   302.6  615.18   341.6   621.7   409.9  632.84   439.2  637.93
   468.5  642.74   478.2  644.99     488  648.25
#Mann= 3 , 0 , 0
       0     .08       0   245.7    .045       0   277.2     .08       0
Bank Sta=245.7,277.2
XS Rating Curve= 0 ,0
Exp/Cntr=0.3,0.1

Type RM Length L Ch R = 1 ,6786.9  ,254.2,257.1,260
XS GIS Cut Line= 2
     1669709.572      538730.099     1669334.038      538418.455
#Sta/Elev= 30
       0  637.84    19.5  636.51    29.3  635.51    48.8  632.59    58.6  630.87
    68.3   628.7    78.1  626.06    87.8  623.08    97.6  620.36   107.4  618.01
   117.1  615.87   136.6  611.95   146.4  610.08   156.2  608.37   165.9  607.08
   201.1604.7225   214.7  603.68   224.5  603.29   233.7604.0298   253.8  607.48
   273.3  609.82   292.8  612.45   302.6   613.8   331.8  618.18   419.7  632.38
   429.4  634.47   439.2  638.14     449  642.97   468.5  653.46     488   664.4
#Mann= 3 , 0 , 0
       0     .08       0   201.1    .045       0   233.7     .06       0
Bank Sta=201.1,233.7
XS Rating Curve= 0 ,0
Exp/Cntr=0.3,0.1

Type RM Length L Ch R = 1 ,6529.8  ,397.6,405.2,412.2
XS GIS Cut Line= 2
     1669862.386      538588.784     1669497.635      538225.046
#Sta/Elev= 30
       0   647.1     9.7  642.82    19.4  640.05    29.2  639.57    48.6   639.4
    58.3  638.73    87.5  635.46   116.6  631.46   126.4  629.24   136.1  626.66
   184.7  612.27   194.4  609.65   204.1  607.72   213.8  606.76     243  605.39
   273.2603.6418   281.9  603.09   291.6  602.89   302.9 603.297     311  603.94
   330.4  606.14   340.2  607.97   369.3  616.13     379  618.15   437.4  626.95
   466.5  632.48   476.2  634.51     486  636.92   495.7  639.82   515.1  646.45
#Mann= 3 , 0 , 0
       0     .06       0   273.2    .045       0   302.9     .06       0
Bank Sta=273.2,302.9
XS Rating Curve= 0 ,0
Exp/Cntr=0.3,0.1

Type RM Length L Ch R = 1 ,6124.5  ,354.5,353.9,353.3
XS GIS Cut Line= 2
     1670070.918      538389.619     1669773.564      537851.654
#Sta/Elev= 30
       0  687.73    19.5  675.06    29.3  668.24    48.8  653.46    58.5  646.42
    68.3  642.48    87.8  640.43    97.6  638.12   117.1  632.24   126.8  630.22
   146.4  627.37   165.9  623.97   175.6  621.75   185.4  618.78   204.9  611.87
   214.6  608.72   224.4  607.02   234.2  606.22   263.4  604.65   312.2  602.81
   328.3602.4484   341.5  602.31   354.9602.7205     361  603.15   429.3  611.87
   478.1  618.87   546.4  629.13   556.1  631.65   565.9  635.92   614.7  663.13
#Mann= 3 , 0 , 0
       0     .06       0   328.3    .045       0   354.9     .06       0
Bank Sta=328.3,354.9
XS Rating Curve= 0 ,0
Exp/Cntr=0.3,0.1

Type RM Length L Ch R = 1 ,5770.6  ,446.9,438.5,429.8
XS GIS Cut Line= 2
     1670360.288      538169.853      1670028.29      537611.314
#Sta/Elev= 30
       0  645.87     9.7  643.54    58.2  630.09    67.9  627.67    77.6  625.82
   135.8  615.99   164.9  610.52   174.6  608.95   184.3  608.02   232.8  605.86
   261.8  604.32   303.6601.6934     320   601.4   327.1601.7281   387.9  606.94
   397.6  608.08   475.2  622.84   484.9  624.78   494.6  627.17     514  632.98
   533.4  638.39   562.5  645.48   581.9  650.61   591.6  653.59   601.3  656.97
     611  660.74   620.7  664.97   630.4  669.73   640.1  675.12   649.8  681.38
#Mann= 3 , 0 , 0
       0     .06       0   303.6    .045       0   327.1     .08       0
Bank Sta=303.6,327.1
XS Rating Curve= 0 ,0
Exp/Cntr=0.3,0.1

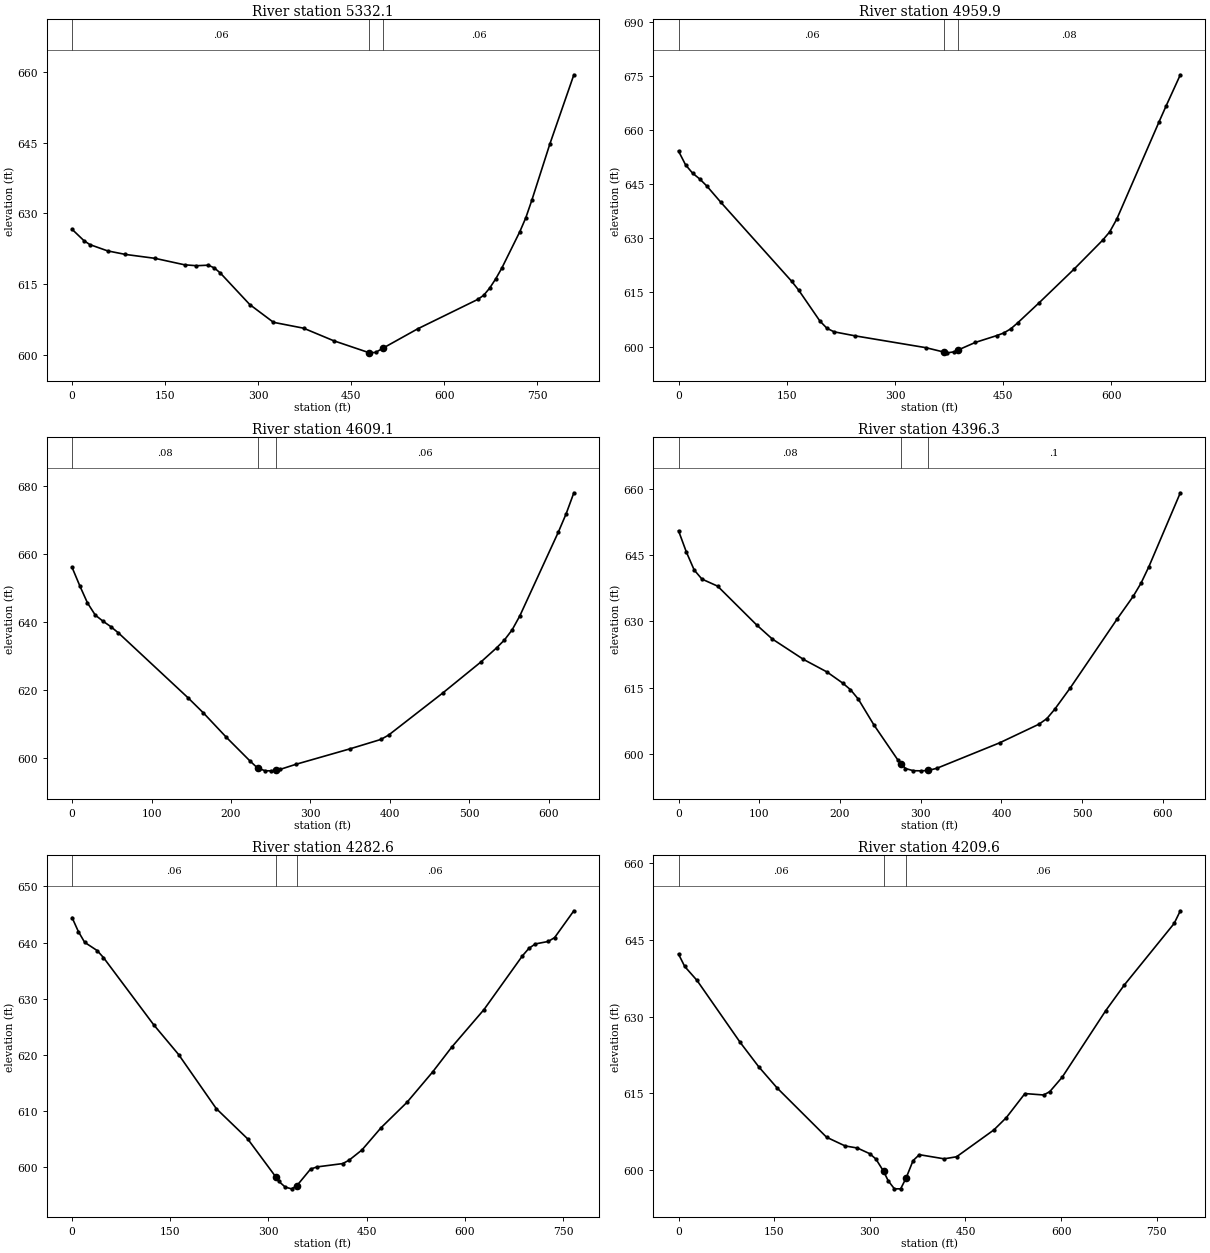
Type RM Length L Ch R = 1 ,5332.1  ,368.1,372.2,376.2
XS GIS Cut Line= 3
     1670511.142      538047.529     1670601.728      537735.583
     1670254.378      537397.994
#Sta/Elev= 30
       0  626.63    19.1  624.23    28.7  623.39    57.3  622.06      86  621.31
   133.8  620.48   181.5  619.11   200.6  618.92   219.7  619.03   229.3  618.46
   238.8  617.41   286.6  610.69   324.8  606.93   373.3  605.69   421.7  603.04
   478.4600.5219   479.8  600.47   489.5  600.56   501.4601.4628   557.3  605.55
   654.2  611.78   663.9  612.67   673.6  614.21   683.3  616.16     693  618.41
     722  626.11   731.7  629.07   741.4  632.78   770.5   644.7   809.2  659.35
#Mann= 3 , 0 , 0
       0     .06       0   478.4    .045       0   501.4     .06       0
Bank Sta=478.4,501.4
XS Rating Curve= 0 ,0
Exp/Cntr=0.3,0.1

Type RM Length L Ch R = 1 ,4959.9  ,349.1,350.9,352.2
XS GIS Cut Line= 2
     1670994.021      537687.602      1670566.94      537138.493
#Sta/Elev= 30
       0  654.14     9.8  650.32    19.6  648.01    29.4  646.42    39.2  644.48
    58.8  639.93   156.8   618.1   166.6  615.63     196  607.08   205.8  605.07
   215.6   604.1   244.9  602.98   342.9  599.71   368.4598.4672   372.3  598.28
   382.1  598.56   387.2599.0394   411.5  601.17   440.9  603.04   450.7  603.77
   460.5  604.92   470.3  606.61   499.7  612.11   548.7  621.54   587.9  629.47
   597.7  631.78   607.5  635.32   666.2  662.29     676   666.7   695.6  675.28
#Mann= 3 , 0 , 0
       0     .06       0   368.4    .045       0   387.2     .08       0
Bank Sta=368.4,387.2
XS Rating Curve= 0 ,0
Exp/Cntr=0.3,0.1

Type RM Length L Ch R = 1 ,4609.1  ,218.3,212.8,207.2
XS GIS Cut Line= 2
     1671224.717      537476.714     1670864.493      536958.039
#Sta/Elev= 30
       0  656.08     9.7  650.67    19.4  645.62    29.2  642.05    38.9  640.26
    48.6  638.68    58.3  636.82   145.7  617.79   165.2  613.31   194.3  606.09
   223.4  599.28   233.2  597.13     234597.0593   242.9  596.28   250.8  596.26
   256.8596.4592   262.3  596.72   281.7  598.18   349.8  602.73   388.6  605.49
   398.3  606.76   466.3  619.11   514.9  628.34   534.3  632.43   544.1  634.72
   553.8   637.7   563.5  641.82   612.1  666.52   621.8  671.84   631.5  678.01
#Mann= 3 , 0 , 0
       0     .08       0     234    .045       0   256.8     .06       0
Bank Sta=234,256.8
XS Rating Curve= 0 ,0
Exp/Cntr=0.3,0.1

Type RM Length L Ch R = 1 ,4396.3  ,97.5,113.7,127.3
XS GIS Cut Line= 3
     1671346.451      537369.563      1671287.21      537185.358
     1670980.236      536887.011
#Sta/Elev= 30
       0  650.59     9.7  645.76    19.4  641.68      29  639.62    48.4  638.02
    96.8  629.21   116.1  626.03   154.8  621.39   183.8  618.55   203.2  616.04
     213  614.52   222.7  612.38   242.1   606.5   271.3  598.67   276.1597.6708
   281.1  596.63   290.8  596.13   300.5   596.1   309.2596.1807     320  596.68
   397.8  602.46   446.4  606.68   456.2  607.94   465.9  610.05   485.4  614.96
   543.7  630.66   563.2   635.7   572.9  638.69   582.6  642.42   621.6  659.21
#Mann= 3 , 0 , 0
       0     .08       0   276.1    .045       0   309.2      .1       0
Bank Sta=276.1,309.2
XS Rating Curve= 0 ,0
Exp/Cntr=0.3,0.1

Type RM Length L Ch R = 1 ,4282.6  ,72.9,72.9,66.5
XS GIS Cut Line= 3
      1671386.29      537345.422     1671282.774      537016.608
     1671043.229      536669.458
#Sta/Elev= 30
       0  644.46     9.6  641.97    19.2  640.05    38.3  638.58    47.9  637.34
   124.5  625.38   162.8  620.04   220.2  610.42   268.1  605.03   311.3598.2195
     316  597.43   325.6  596.42   335.2  596.11   343.3596.6642   364.3  599.63
   374.2  600.02   413.4  600.61   423.2  601.22   442.8  603.04   472.2  607.03
   511.5  611.52   550.7  616.93   580.1  621.39   629.2  628.06     688  637.65
   697.8  638.97   707.6  639.76   727.3   640.2   737.1  640.89   766.5  645.67
#Mann= 3 , 0 , 0
       0     .06       0   311.3    .045       0   343.3     .06       0
Bank Sta=311.3,343.3
XS Rating Curve= 0 ,0
Exp/Cntr=0.3,0.1

Type RM Length L Ch R = 1 ,4209.6  ,289.6,305.6,329
XS GIS Cut Line= 3
     1671444.074      537310.407     1671342.408      536987.469
     1671087.779       536618.46
#Sta/Elev= 30
       0  642.22     9.7  639.81      29  637.08    96.7  624.96   125.8  620.19
   154.8  616.03   232.2  606.42   261.2  604.72   280.5  604.31   299.9   603.2
   309.5  602.16   321.5 599.772   328.9  597.88   338.6  596.33   348.3  596.33
   356.8 598.429   367.8  601.85   377.6  603.01   416.5   602.2     436   602.6
   494.5  607.85     514  610.25   543.2  614.96   572.5  614.68   582.2  615.34
   601.7  618.17   669.9  631.17   699.2  636.21   777.2  648.22   786.9   650.7
#Mann= 3 , 0 , 0
       0     .06       0   321.5    .045       0   356.8     .06       0
Bank Sta=321.5,356.8
XS Rating Curve= 0 ,0
Exp/Cntr=0.3,0.1

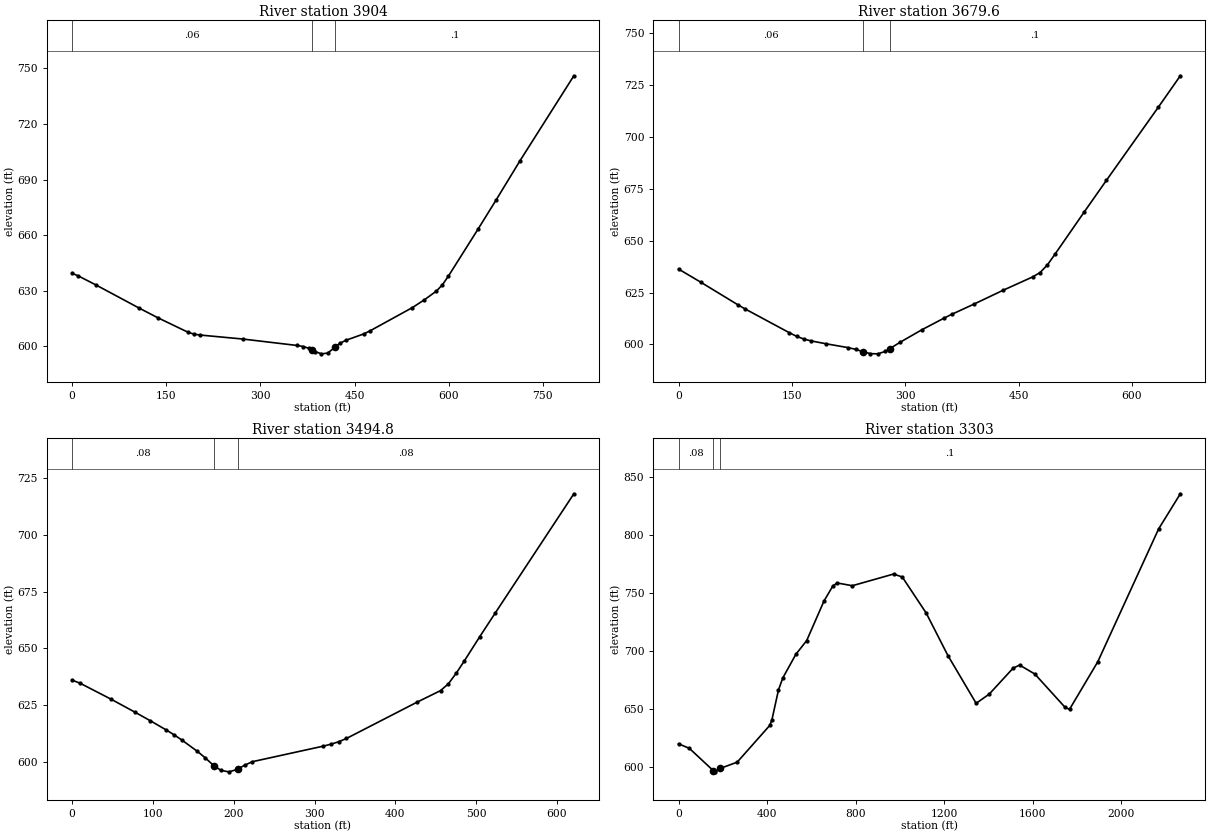
Type RM Length L Ch R = 1 ,3904    ,220.4,224.5,228.1
XS GIS Cut Line= 4
     1671509.168      537270.963     1671531.907      537077.848
     1671623.283      536732.309     1671754.499      536522.435
#Sta/Elev= 30
       0  639.48     9.7  638.11    38.9  633.04     107  620.68   136.1  615.58
   184.7  607.68   194.4  606.64   204.1  606.16   271.7  604.02   358.7  600.53
   368.3  599.97     378  598.94   381.8598.2473   387.6  597.19   397.3  596.02
     407  596.42   418.7599.4662   426.3  601.66     436   603.3   464.9   606.8
   474.6  608.41   542.2  620.98   561.4  625.21   580.4  629.88     590  633.26
   599.5  637.95   647.1   663.5   675.6  679.07   713.7  700.27   799.4  746.06
#Mann= 3 , 0 , 0
       0     .06       0   381.8    .045       0   418.7      .1       0
Bank Sta=381.8,418.7
XS Rating Curve= 0 ,0
Exp/Cntr=0.3,0.1

Type RM Length L Ch R = 1 ,3679.6  ,193.3,184.7,176.3
XS GIS Cut Line= 2
     1671652.169      537258.278      1671917.15      536649.463
#Sta/Elev= 30
       0  636.29    29.3  629.99    78.1  619.19    87.9  617.14   146.5  605.68
   156.2  603.94     166  602.58   175.8   601.7   195.3  600.33   224.6  598.48
   234.4  597.66   243.5596.5811   253.9  595.59   263.6   595.5   273.4  596.63
   279.3597.9063   292.9  601.01   322.2  607.12   351.5  612.71   361.3  614.47
   390.6  619.37   429.6   626.1   468.7  632.52   478.5  634.63   488.2  638.32
     498  643.36     537  663.84   566.3  679.02   634.7  714.06     664  729.27
#Mann= 3 , 0 , 0
       0     .06       0   243.5    .045       0   279.3      .1       0
Bank Sta=243.5,279.3
XS Rating Curve= 0 ,0
Exp/Cntr=0.3,0.1

Type RM Length L Ch R = 1 ,3494.8  ,192.5,191.8,189.8
XS GIS Cut Line= 2
     1671896.801      537297.692     1671954.491      536679.522
#Sta/Elev= 30
       0  635.91     9.7   634.6    48.5  627.46    77.6  621.82      97  617.96
   116.4  613.95   126.1  611.82   135.8  609.49   155.2  604.44   164.9  601.58
   174.6  598.41   176.1598.0466   184.3  596.06     194  595.44   203.7  596.42
   204.7596.6179   213.4  598.34   223.1  599.92   310.4  606.75   320.1  607.62
   329.8  608.71   339.5  610.17   426.8  626.18   455.9  631.29   465.6  634.28
   475.3  638.96     485  644.19   504.4  655.08   523.8  665.65   620.9  718.18
#Mann= 3 , 0 , 0
       0     .08       0   176.1    .045       0   204.7     .08       0
Bank Sta=176.1,204.7
XS Rating Curve= 0 ,0
Exp/Cntr=0.3,0.1

Type RM Length L Ch R = 1 ,3303    ,256.4,284,310.8
XS GIS Cut Line= 2
     1672092.146      537239.417     1672194.532      534975.877
#Sta/Elev= 30
       0  619.67      49   615.7   157.7596.3792   166.8  595.46   188.1598.4106
   264.8   603.8     412  635.52   421.8  640.45   451.2  666.05   470.8  676.45
   529.7  696.82   578.7  708.71   657.2  742.99   696.4  755.66     716  758.41
   784.7  756.02   971.1  766.11  1010.3  763.53  1118.2  732.49  1216.3   695.8
  1343.8  654.58  1402.7  662.47  1510.6  684.87    1540  687.56  1608.7  679.87
    1746  650.97  1765.6  649.42  1893.1  690.43  2167.8  805.02  2265.8  835.34
#Mann= 3 , 0 , 0
       0     .08       0   157.7    .045       0   188.1      .1       0
Bank Sta=157.7,188.1
XS Rating Curve= 0 ,0
Exp/Cntr=0.3,0.1