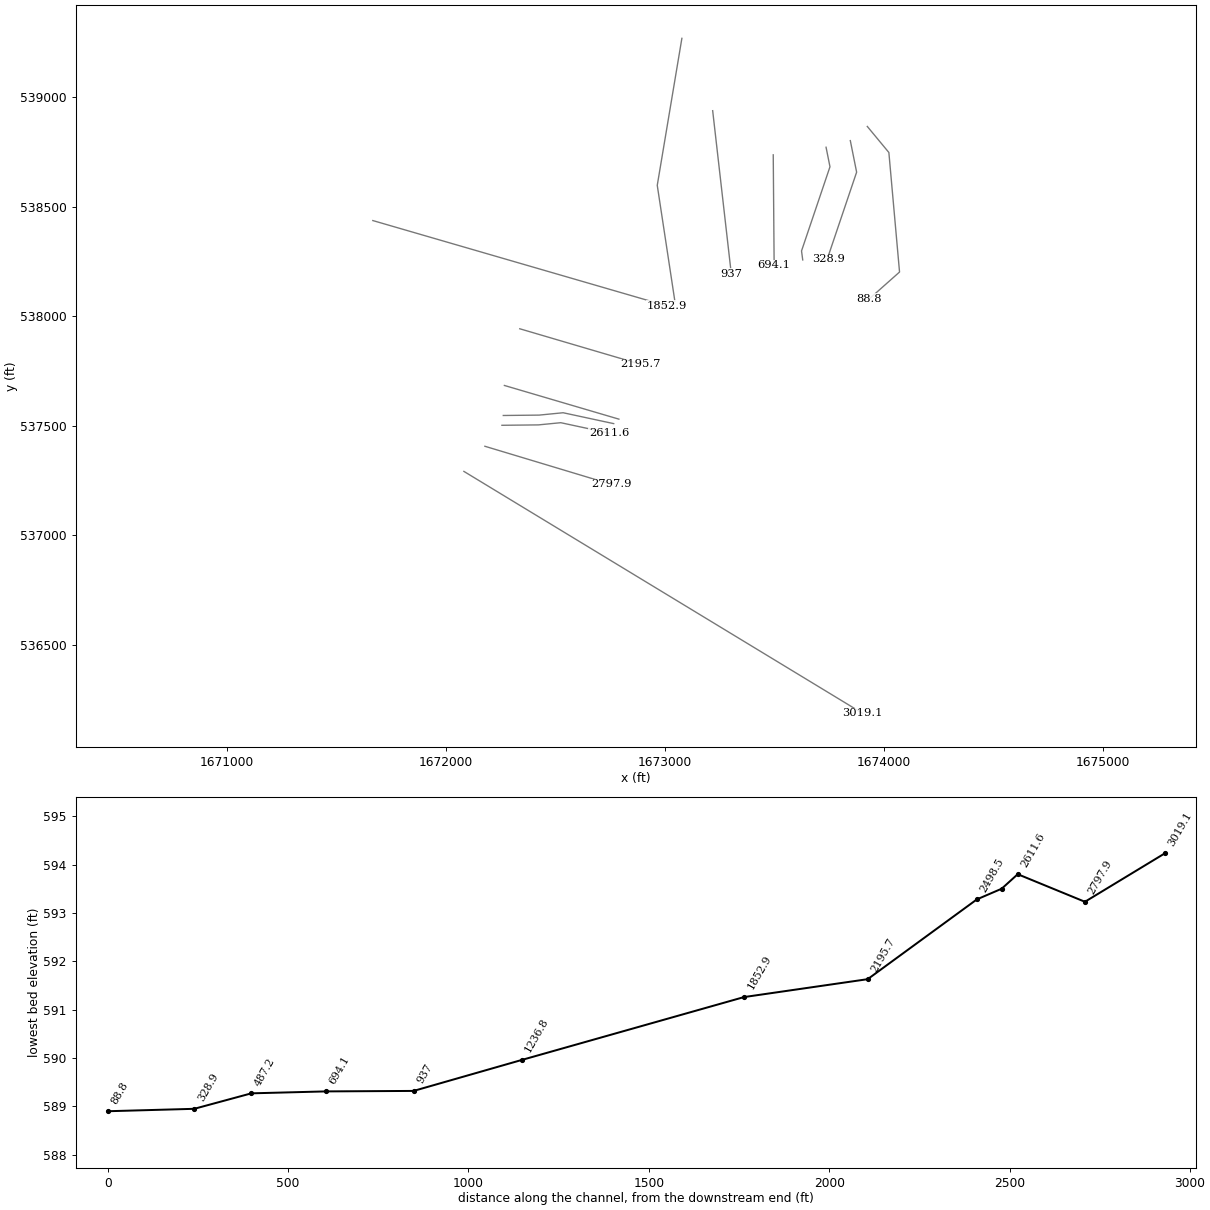
HEC-RAS study NP13.prj: NP13

--- NP13.g01 (geometry) --- (continued)

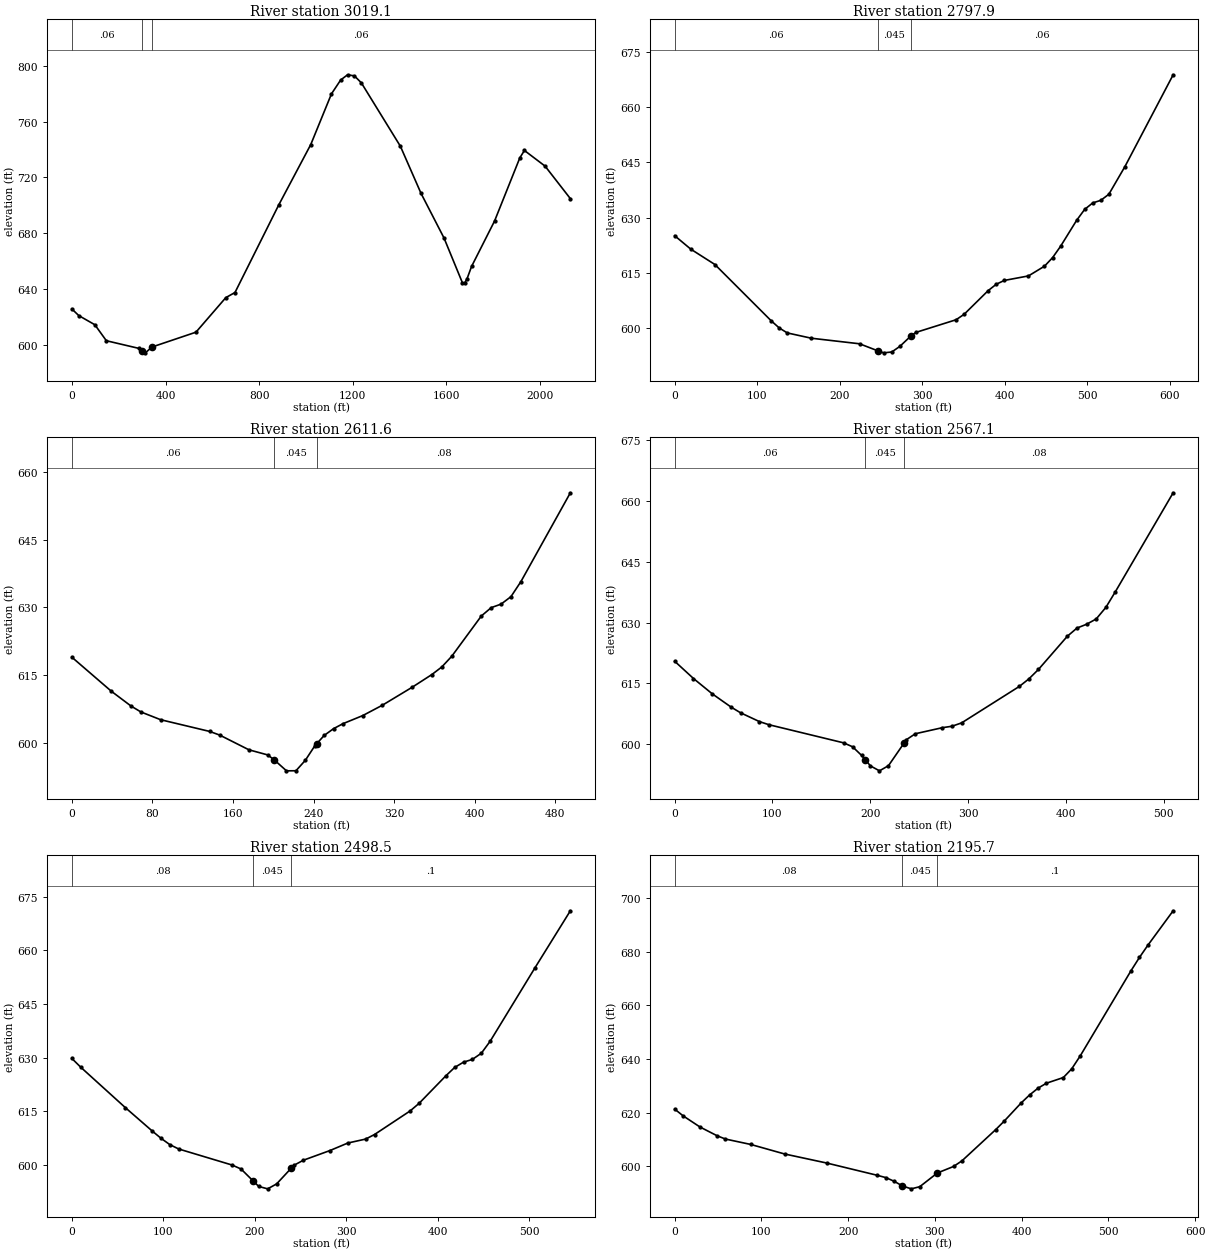
Type RM Length L Ch R = 1 ,3019.1  ,214.1,221.2,228
XS GIS Cut Line= 2
     1672083.246      537291.879     1673903.496      536186.459
#Sta/Elev= 30
       0  625.67    29.4  620.94    98.1  614.37   147.2  602.91   284.6  597.49
   301.6595.3159     314  594.23   341.8598.3876     530  609.04   657.5  633.81
   696.8  637.49   883.2  700.11  1020.6   743.6    1109  779.94  1148.2  789.84
  1177.7   793.6  1207.1   792.8  1236.6  787.82  1403.4  742.36  1491.7  708.54
  1589.8  676.57  1668.4  644.47  1678.2  644.44    1688  647.26  1707.6  656.19
  1805.8  688.76  1913.7  734.03  1933.3  739.33  2021.7  728.09  2129.6  704.79
#Mann= 3 , 0 , 0
       0     .06       0   301.6    .045       0   341.8     .06       0
Bank Sta=301.6,341.8
XS Rating Curve= 0 ,0
Exp/Cntr=0.3,0.1

Type RM Length L Ch R = 1 ,2797.9  ,175.1,186.3,197.5
XS GIS Cut Line= 2
     1672179.091      537406.664     1672757.287      537232.459
#Sta/Elev= 30
       0  625.05    19.5   621.4    48.7  617.23   116.9  601.94   126.6     600
   136.4  598.64   165.6   597.2     224  595.69   245.7593.8099   253.2  593.23
     263  593.46   272.7  594.97   286.3597.8408   292.2  598.78   340.9  602.22
   350.6  603.69   379.8  610.14   389.6  611.87   399.3   612.9   428.6  614.13
     448  616.77   457.8  619.09   467.5  622.18     487  629.25   496.7  632.21
   506.5  633.97   516.2  634.66     526  636.32   545.4  643.81   603.9  668.78
#Mann= 3 , 0 , 0
       0     .06       0   245.7    .045       0   286.3     .06       0
Bank Sta=245.7,286.3
XS Rating Curve= 0 ,0
Exp/Cntr=0.3,0.1

Type RM Length L Ch R = 1 ,2611.6  ,44.9,44.5,44.3
XS GIS Cut Line= 4
     1672256.828       537502.52     1672423.234      537504.284
     1672525.485      537514.348     1672746.221      537466.822
#Sta/Elev= 30
       0  618.97    39.2  611.43    58.7  608.16    68.5  606.85    88.1  605.13
     137  602.52   146.8  601.72   175.8  598.46   194.4  597.33   200.9596.2374
   213.1   593.8   222.5  593.82   231.8  596.13   241.1   599.3   243.3599.8477
   250.5  601.64   259.8  603.14   269.2  604.25   288.8  606.04   308.4  608.35
   337.9  612.32   357.5  615.14   367.3  616.81   377.2  619.18   406.6  628.11
   416.4  629.96   426.2  630.74     436  632.39   445.9  635.73     495  655.41
#Mann= 3 , 0 , 0
       0     .06       0   200.9    .045       0   243.3     .08       0
Bank Sta=200.9,243.3
XS Rating Curve= 0 ,0
Exp/Cntr=0.3,0.1

Type RM Length L Ch R = 1 ,2567.1  ,79.3,68.6,57.9
XS GIS Cut Line= 4
      1672263.08      537547.311     1672426.613      537549.044
     1672536.216      537559.832     1672766.983      537510.146
#Sta/Elev= 30
       0  620.46    19.2  616.22    38.5  612.43    57.7  609.18    67.3  607.79
    86.6  605.62    96.2  604.86   172.7  600.39   181.9  599.42   191.1   597.3
   194.9596.2184   200.2  594.71   209.4   593.5   218.6  594.77   234.9600.4633
     237  601.18   246.1  602.63   273.7  604.12   283.5  604.47   293.4   605.3
   352.4  614.27   362.2  616.13     372  618.46   401.5  626.62   411.4  628.64
   421.2  629.57     431  630.87   440.9  633.72   450.7  637.61   509.7  661.92
#Mann= 3 , 0 , 0
       0     .06       0   194.9    .045       0   234.9     .08       0
Bank Sta=194.9,234.9
XS Rating Curve= 0 ,0
Exp/Cntr=0.3,0.1

Type RM Length L Ch R = 1 ,2498.5  ,301.5,302.8,302
XS GIS Cut Line= 2
     1672268.154       537684.46     1672790.829      537530.563
#Sta/Elev= 30
       0  629.74     9.7  627.29    58.4     616    87.6   609.5    97.3  607.44
     107  605.65   116.8  604.42   175.1  599.94   184.9  598.83   198.4 595.412
   204.3  593.94     214  593.28   223.8  594.66   239.6599.0133   243.2  599.93
     253  601.28   282.2     604   301.6  606.09   321.1   607.2   330.8  608.47
   369.7  615.06   379.5  617.18   408.6  624.84   418.4  627.23   428.1  628.71
   437.8  629.48   447.6  631.21   457.3  634.59   505.9  654.97   544.9  671.05
#Mann= 3 , 0 , 0
       0     .08       0   198.4    .045       0   239.6      .1       0
Bank Sta=198.4,239.6
XS Rating Curve= 0 ,0
Exp/Cntr=0.3,0.1

Type RM Length L Ch R = 1 ,2195.7  ,341.2,342.8,342
XS GIS Cut Line= 2
     1672338.281      537943.463     1672889.622      537781.126
#Sta/Elev= 30
       0  621.32     9.7  618.81    29.2  614.65    48.7  611.43    58.4  610.18
    87.7  608.16   126.6  604.62   175.4  601.23   233.8  596.65   243.5  595.81
   253.3   594.4   262.6592.6934   272.8  591.63   282.5  592.42   302.8 597.528
   321.5  599.96   331.2  602.06   370.2  613.71   379.9  616.85   399.4   623.6
   409.1  626.57   418.9  629.12   428.6  630.97   448.1  633.08   457.8  636.34
   467.6  641.16     526   672.8   535.8  677.79   545.5  682.33   574.7  695.18
#Mann= 3 , 0 , 0
       0     .08       0   262.6    .045       0   302.8      .1       0
Bank Sta=262.6,302.8
XS Rating Curve= 0 ,0
Exp/Cntr=0.3,0.1

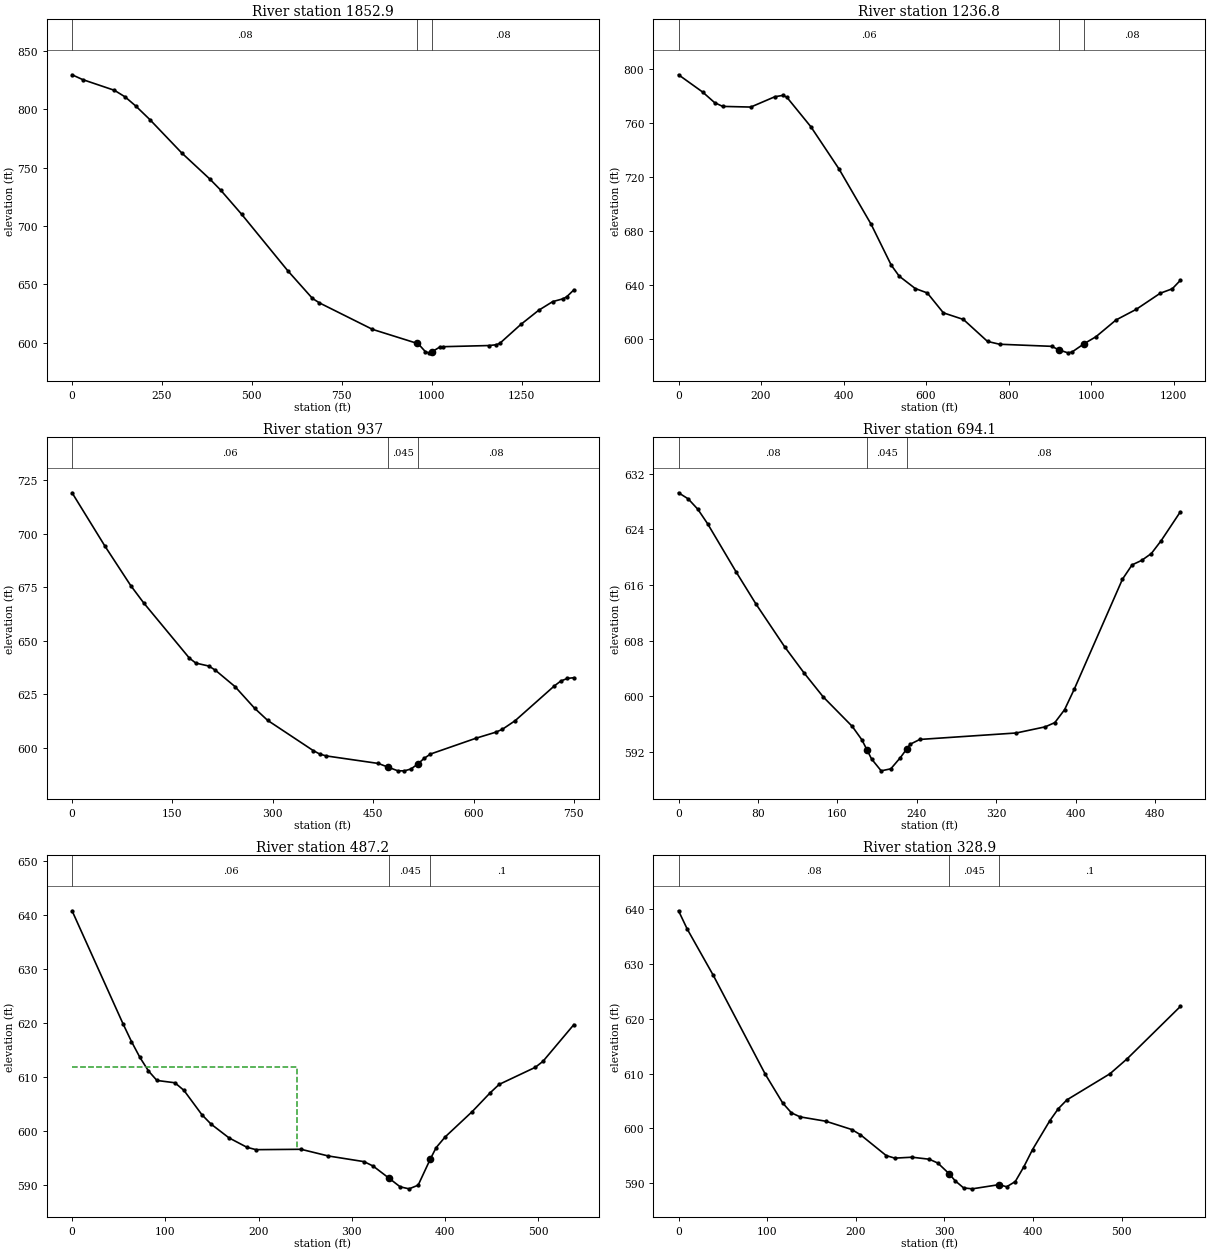
Type RM Length L Ch R = 1 ,1852.9  ,642.8,616.1,582.5
XS GIS Cut Line= 2
     1671667.487      538437.788     1673007.608      538048.427
#Sta/Elev= 30
       0   829.6    29.5  825.48   117.9  816.27   147.4  810.67   176.9  802.89
   216.2  791.23   304.7  762.69   383.3  740.18   412.8  730.91   471.7  709.99
   599.5  661.77   668.3  637.97   687.9  634.08   835.4   611.4   960.1599.3331
   963.1  598.88   982.8  592.19   992.6  591.26  1001.3592.2276  1022.1  596.12
  1031.9  596.53  1159.7  597.52  1179.3  598.19  1189.2   599.3  1248.1  615.62
  1297.3  627.66  1336.6  635.16    1366  637.64  1375.9  639.39  1395.5  645.23
#Mann= 3 , 0 , 0
       0     .08       0   960.1    .045       0  1001.3     .08       0
Bank Sta=960.1,1001.3
XS Rating Curve= 0 ,0
Exp/Cntr=0.3,0.1

Type RM Length L Ch R = 1 ,1236.8  ,301.5,299.8,299.8
XS GIS Cut Line= 3
     1673078.295      539270.235      1672965.89      538598.715
     1673046.313      538069.271
#Sta/Elev= 30
       0  795.57    58.4  782.82    87.5  774.96     107  772.19   175.1   771.7
   233.4  779.32   252.9  780.34   262.6  778.95     321  757.06   389.1  725.88
   466.9  685.01   515.5  654.87     535  646.64   573.9  637.51     603  634.25
     642  619.54   690.6  614.64     749   598.4   778.2  596.32   904.8  594.77
   921.6592.1948   943.8  589.96   953.5   590.5   983.4 596.756  1011.9  601.88
  1060.6  614.28  1109.3  622.09  1167.7  634.03  1196.9  637.32  1216.4  643.56
#Mann= 3 , 0 , 0
       0     .06       0   921.6    .045       0   983.4     .08       0
Bank Sta=921.6,983.4
XS Rating Curve= 0 ,0
Exp/Cntr=0.3,0.1

Type RM Length L Ch R = 1 ,937     ,244.2,242.8,240.8
XS GIS Cut Line= 2
     1673218.835      538939.684      1673303.82      538194.621
#Sta/Elev= 30
       0  719.17    48.7  694.47    87.6  675.86   107.1  667.72   175.3  641.96
     185  639.63   204.5  638.25   214.3  636.28   243.5  628.66   272.7  618.58
   292.2  612.91   360.3   598.8   370.1  597.17   379.8  596.29   457.7  592.77
   471.4591.1409   486.9  589.33   496.7  589.32   506.4  590.18   516.4592.4359
   525.9  595.09   535.6  597.16   603.8  604.57     633  607.35   642.8  608.66
   662.2  612.75   720.7  628.97   730.4  631.26   740.2  632.48   749.9  632.82
#Mann= 3 , 0 , 0
       0     .06       0   471.4    .045       0   516.4     .08       0
Bank Sta=471.4,516.4
XS Rating Curve= 0 ,0
Exp/Cntr=0.3,0.1

Type RM Length L Ch R = 1 ,694.1   ,217.1,206.9,197.7
XS GIS Cut Line= 2
     1673495.332       538737.98     1673499.445      538232.593
#Sta/Elev= 30
       0  629.26     9.7  628.39    19.4   626.9    29.2  624.83    58.3  617.82
    77.8  613.32   106.9  607.13   126.4  603.38   145.8  599.92     175  595.69
   184.7  593.76   189.6592.3759   194.4  591.02   204.1  589.31   213.8   589.6
   223.5  591.22   229.7592.4283   233.3  593.13     243  593.82   340.2  594.75
   369.3  595.63     379  596.24   388.8  598.09   398.5  601.02   447.1  616.84
   456.8   618.9   466.5  619.55   476.2  620.53     486  622.36   505.4  626.52
#Mann= 3 , 0 , 0
       0     .08       0   189.6    .045       0   229.7     .08       0
Bank Sta=189.6,229.7
XS Rating Curve= 0 ,0
Exp/Cntr=0.3,0.1

Type RM Length L Ch R = 1 ,487.2   ,157,158.4,156.6
XS GIS Cut Line= 4
     1673736.446      538772.695     1673754.299      538683.464
     1673624.449      538299.017     1673629.932      538257.921
#Sta/Elev= 30
       0  640.81    54.6  619.88    63.7  616.58    72.8  613.62    81.9  611.13
      91  609.36   110.3  608.93     120  607.52   139.3     603     149  601.28
   168.3  598.72   187.6  596.97   197.3  596.53   245.6   596.6   274.6  595.37
   313.2  594.31   322.9  593.49   340.1591.2244   351.9  589.64   361.5  589.27
   371.2  589.95   384.2594.7797   390.5  596.91   400.2   598.9   429.2  603.59
   448.5  607.08   458.1  608.63   496.8  611.79   505.1  612.91   538.2  619.71
#Mann= 3 , 0 , 0
       0     .06       0   340.1    .045       0   384.2      .1       0
#XS Ineff= 2 , 0
          240.86  611.88
Permanent Ineff=
       F       F
Bank Sta=340.1,384.2
XS Rating Curve= 0 ,0
Exp/Cntr=0.3,0.1

Type RM Length L Ch R = 1 ,328.9   ,227.2,240,252.7
XS GIS Cut Line= 4
     1673847.136      538803.023     1673875.969      538658.914
     1673745.395      538272.325     1673746.901       538261.04
#Sta/Elev= 30
       0  639.76     9.8  636.42    39.2  627.97      98  609.87   117.6  604.63
   127.4  602.84   137.2   602.1   166.4   601.3   195.5  599.79   205.3  598.84
   234.4  595.03   244.1  594.56   263.6  594.73     283  594.36   292.7  593.66
   305.6591.6864   312.1  590.44   321.8  589.12   331.6  588.95   361.7589.7157
   370.4  589.33   380.1  590.28   389.8  592.99   399.6  596.13     419  601.38
   428.7   603.6   438.4  605.21     487  609.98   506.4  612.72   566.4  622.27
#Mann= 3 , 0 , 0
       0     .08       0   305.6    .045       0   361.7      .1       0
Bank Sta=305.6,361.7
XS Rating Curve= 0 ,0
Exp/Cntr=0.3,0.1

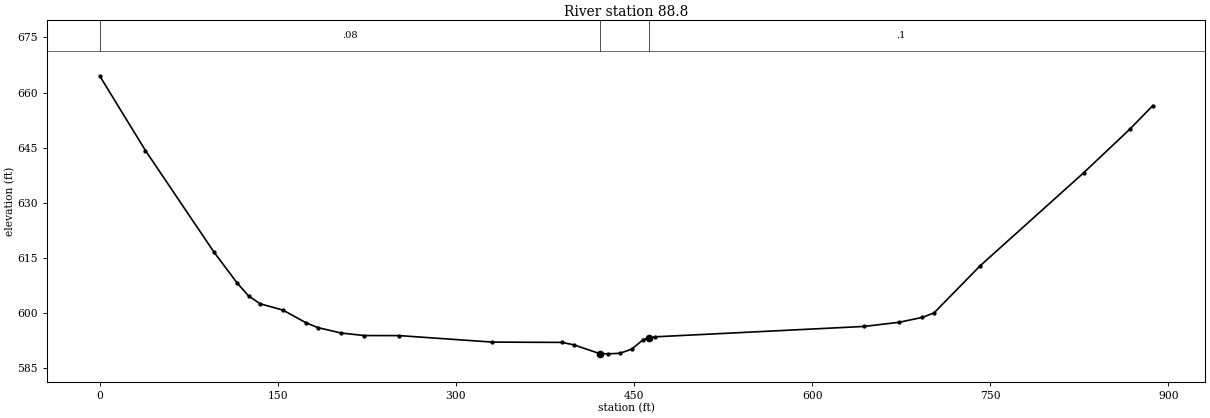
Type RM Length L Ch R = 1 ,88.8    ,71.8,88.8,104.8
XS GIS Cut Line= 4
     1673924.692      538867.662     1674023.152      538748.707
     1674071.852      538202.623     1673934.043      538080.324
#Sta/Elev= 30
       0  664.57    38.6  644.22    96.5  616.49   115.8  608.19   125.5  604.63
   135.1  602.54   154.4   600.8     174  597.32   183.8  596.04   203.4  594.56
     223  593.88   252.3  593.86   330.6   592.1   389.4  592.01   399.2  591.36
   421.3588.9445   428.5   588.9   438.3  589.06   448.1  590.19   457.9   592.8
   462.5593.1426   467.7  593.53   643.9  596.36   673.3  597.49   692.9  598.82
   702.7  600.04   741.5  612.85   828.7  638.17   867.5  650.01   886.9  656.43
#Mann= 3 , 0 , 0
       0     .08       0   421.3    .045       0   462.5      .1       0
Bank Sta=421.3,462.5
XS Rating Curve= 0 ,0
Exp/Cntr=0.3,0.1

Chan Stop Cuts=-1
Use User Specified Reach Order=0
Composite Channel Slope=5